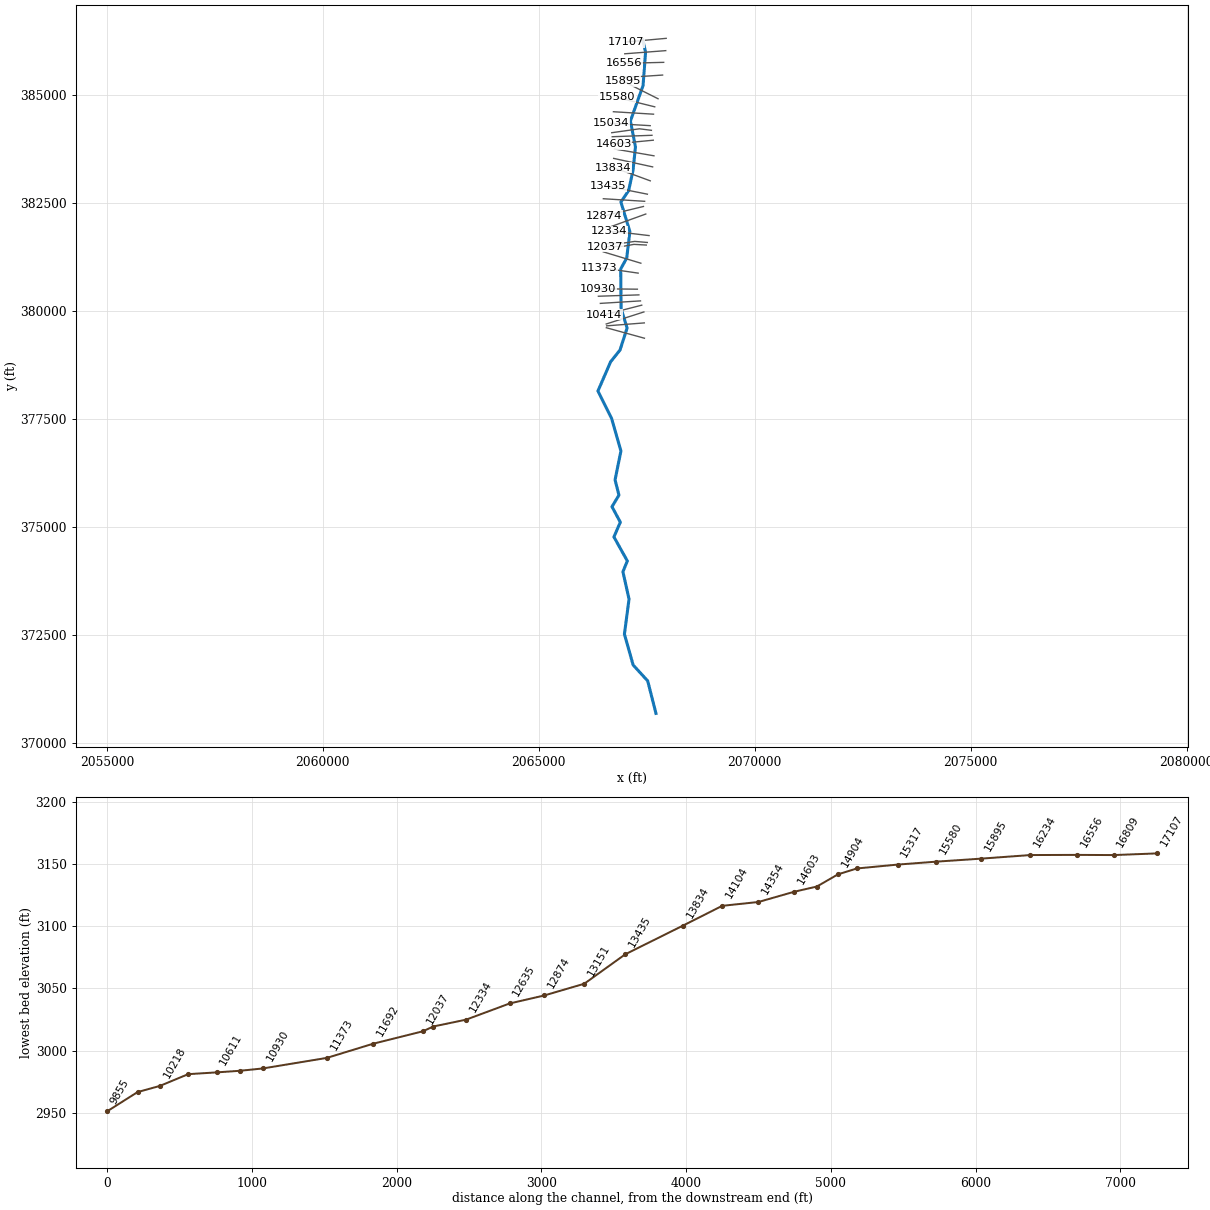
--- BROWNCK.prj (project) ---

Proj Title=BROWNCK
Current Plan=p01
Default Exp/Contr=0,0
English Units
Geom File=g01
Flow File=f01
Plan File=p01
BEGIN DESCRIPTION:
Stream Name- Brown Creek
Flood Zone: Zone A
Greenbrier County, WV
County-Wide Study
WVDHSEM-2018-3, Flood Risk Project
HEC-RAS Version: 5.0.7
General Notes:
For the Hydrology regression was used.
END DESCRIPTION:
DSS Export Rating Curves= 0
DSS Export Rating Curve Sorted= 0
DSS Export Volume Flow Curves= 0
DXF OffsetX= 0
DXF OffsetY= 0
DXF ScaleX= 0
DXF ScaleY= 0

--- BROWNCK.p01 (plan) ---

Plan Title=Floodplain
Program Version=5.07
Short Identifier=Floodplain
Geom File=g01
Flow File=f01
Subcritical Flow
K Sum by GR= 0
Std Step Tol= 0.01
Critical Tol= 0.01
Num of Std Step Trials= 20
Max Error Tol= 0.3
Flow Tol Ratio= 0.001
Split Flow NTrial= 30
Split Flow Tol= 0.02
Split Flow Ratio= 0.02
Log Output Level= 0
Friction Slope Method= 1
Unsteady Friction Slope Method= 2
Unsteady Bridges Friction Slope Method= 1
Parabolic Critical Depth
Global Vel Dist= 0 , 0 , 0
Global Log Level= 0
CheckData=True
Encroach Param=-1 ,0,0, 0
Mapping Interval=1HOUR
Computation Time Step Use Courant=        0
Computation Time Step Use Time Series=    0
Computation Time Step Count To Double=0
Computation Time Step Max Doubling=0
Computation Time Step Max Halving=0
Computation Time Step Residence Courant=0
Run HTab= 0
Run UNet= 0
Run Sediment= 0
Run PostProcess= 0
Run WQNet= 0
Run RASMapper=-1
UNET Theta= 0
UNET Theta Warmup= 0
UNET ZTol= 0
UNET ZSATol= 0
UNET MxIter= 0
UNET Max Iter WO Improvement= 0
UNET MaxInSteps= 0
UNET DtIC= 0
UNET DtMin= 0
UNET MaxCRTS= 0
UNET WFStab= 0
UNET SFStab= 0
UNET WFX= 1
UNET SFX= 1
UNET 1D Methodology=Finite Difference
UNET DSS MLevel= 1
UNET Pardiso=0
UNET DZMax Abort= 0
UNET Use Existing IB Tables= 0
UNET Froude Reduction=False
UNET Froude Limit= 0
UNET Froude Power= 0
UNET D1 Cores= 0
UNET D2 Coriolis=0
UNET D2 Cores= 0
UNET D2 Theta= 1
UNET D2 Theta Warmup= 1
UNET D2 Z Tol= 0.01
UNET D2 Volume Tol= 0.01
UNET D2 Max Iterations= 20
UNET D2 Equation= 0
UNET D2 RampUpFraction=0.1
UNET D2 TimeSlices= 1
UNET D2 BCVolumeCheck=0
UNET D1D2 MaxIter= 0
UNET D1D2 ZTol=0.01
UNET D1D2 QTol=0.1
UNET D1D2 MinQTol=1
Write IC File= 0
Write IC File at Fixed DateTime=0
Write IC File at Sim End=0
Echo Input=False
Echo Parameters=False
Echo Output=False
Write Detailed= 0
HDF Write Warmup=0
HDF Write Time Slices=0
HDF Flush=0
HDF Face Node Velocities=0
HDF Compression= 1
HDF Chunk Size= 1
HDF Spatial Parts= 1
HDF Use Max Rows=0
HDF Fixed Rows= 1
Calibration Method= 0
Calibration Iterations= 20
Calibration Max Change=0.05
Calibration Tolerance=0.2
Calibration Maximum=1.5
Calibration Minimum=0.5
Calibration Optimization Method= 1
WQ AD Non Conservative
WQ ULTIMATE=-1
WQ Max Comp Step=1HOUR
WQ Output Interval=15MIN
WQ Output Selected Increments= 0
WQ Output face flow=0
WQ Output face velocity=0
WQ Output face area=0
WQ Output face dispersion=0
WQ Output cell volume=0
WQ Output cell surface area=0
WQ Output cell continuity=0
WQ Output cumulative cell continuity=0
WQ Output face conc=0
WQ Output face dconc_dx=0
WQ Output face courant=0
WQ Output face peclet=0
WQ Output face adv mass=0
WQ Output face disp mass=0
WQ Output cell mass=0
WQ Output cell source sink temp=0
WQ Output nsm pathways=0
WQ Output nsm derived pathways=0
WQ Output MaxMinRange=-1
WQ Daily Max Min Mean=-1
WQ Daily Range=0
WQ Daily Time=0
WQ Create Restart=0
WQ Fixed Restart=0
WQ System Summary=0
WQ Write To DSS=0
WQ Use Fixed Temperature=0
Sorting and Armoring Iterations= 10
XS Update Threshold= 0.02
Bed Roughness Predictor= 0
Hydraulics Update Threshold= 0.02
Energy Slope Method= 1
Volume Change Method= 1
Sediment Retention Method= 0
XS Weighting Method= 0
Number of US Weighted Cross Sections= 1
Number of DS Weighted Cross Sections= 1
Upstream XS Weight=0
Main XS Weight=1
Downstream XS Weight=0
Number of DS XS's Weighted with US Boundary= 1
Upstream Boundary Weight= 1
Weight of XSs Associated with US Boundary= 0
Number of US XS's Weighted with DS Boundary= 1
Downstream Boundary Weight= 0.5
Weight of XSs Associated with DS Boundary= 0.5
Percentile Method= 0
Sediment Output Level= 3
Mass or Volume Output= 0
Output Increment Type= 1
Profile and TS Output Increment= 1
XS Output Flag= 0
XS Output Increment= 10
Write Gradation File= 0
Read Gradation Hotstart= 0
Write HDF5 File= 1
Write Binary Output= 1
Write DSS Sediment File= 0
SV Curve= 0
Specific Gage Flag= 0

--- BROWNCK.f01 (steady flow) ---

Flow Title=H3a_CombinedFlows
Program Version=5.07
Number of Profiles= 6
Profile Names=f1p,f10p,f4p,f2p,f02p,f1pplus
River Rch & RM=BROWNCK,Main            ,17107
     678     360     478     575     944    1000
River Rch & RM=BROWNCK,Main            ,14354
     810     434     573     688    1120    1200
River Rch & RM=BROWNCK,Main            ,13151
     909     489     645     773    1260    1340
River Rch & RM=BROWNCK,Main            ,11692
    1030     555     730     873    1420    1520
River Rch & RM=BROWNCK,Main            ,8394
    1240     677     888    1060    1710    1840
River Rch & RM=BROWNCK,Main            ,4225
    1410     773    1010    1210    1940    2090
Boundary for River Rch & Prof#=BROWNCK,Main            , 1
Up Type= 0
Dn Type= 3
Dn Slope=0.02745
Boundary for River Rch & Prof#=BROWNCK,Main            , 2
Up Type= 0
Dn Type= 3
Dn Slope=0.02745
Boundary for River Rch & Prof#=BROWNCK,Main            , 3
Up Type= 0
Dn Type= 3
Dn Slope=0.02745
Boundary for River Rch & Prof#=BROWNCK,Main            , 4
Up Type= 0
Dn Type= 3
Dn Slope=0.02745
Boundary for River Rch & Prof#=BROWNCK,Main            , 5
Up Type= 0
Dn Type= 3
Dn Slope=0.02745
Boundary for River Rch & Prof#=BROWNCK,Main            , 6
Up Type= 0
Dn Type= 3
Dn Slope=0.02745
DSS Import GetInterval= 0
DSS Import GetPeak= 0
DSS Import FillOption= 0

--- BROWNCK.g01 (geometry) ---

Geom Title=Geometry
Program Version=5.07

River Reach=BROWNCK         ,Main
Reach XY= 30
2067406.84428637386265.0355501472067472.50295727385987.455412015
2067414.19700004385209.3400000182067121.73599999384389.812999994
2067238.49800001383789.371000007     2067181.455383242.753999993
2067080.73200004382779.3810000122066901.06400003382513.423000008
2067108.79100002381830.4689999972067035.66815172381215.150810778
2066896.96820934380965.3808064612066905.89099999 380049.00500001
     2067044.654379596.0690000062066880.97500004379086.979000002
2066662.01100002378812.6770000012066369.77700002378137.913000017
2066685.30299999377504.5729999992066901.90300001376749.126000017
2066766.21700002376081.9200000172066855.68100004375727.342999995
2066695.11300002375458.2689999942066888.32900001375100.864999995
2066739.46100004374759.8920000052067051.04900001374202.398000002
2066947.97400002373954.5010000022067089.63800003373320.090000004
2066982.71699999372509.7039999962067184.59700002371794.214000016
2067521.83200003371426.0699999932067712.75670351370674.459629923

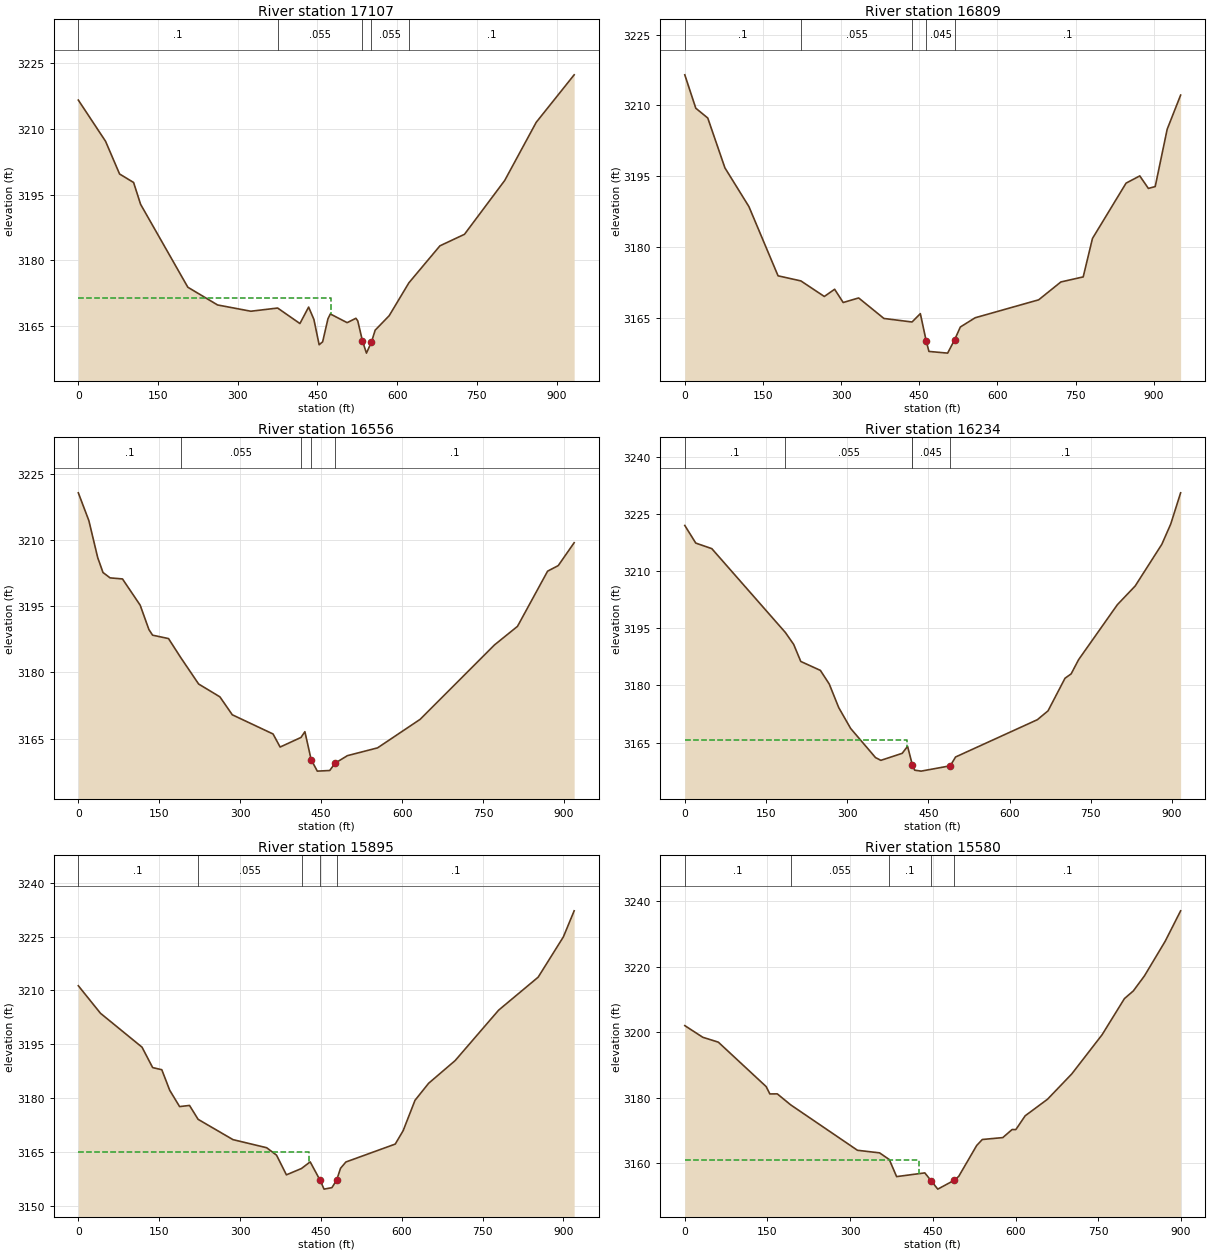
Type RM Length L Ch R = 1 ,17107   ,297.9,297.9,297.9
XS GIS Cut Line= 2
2067950.07722403386303.4898076532067020.82316288386218.640426931
#Sta/Elev= 30
       0 3216.61    51.3 3207.19    77.6 3199.73     104 3197.79   117.2  3192.8
   206.1 3173.86   262.1 3169.81   324.7 3168.38  375.07 3169.11     417 3165.57
   433.4 3169.33   443.3 3166.52   453.2 3160.72   459.8  3161.4   469.7 3166.62
   474.2 3167.76   505.9 3165.77   522.4 3166.77   525.9 3166.16   534.6 3161.66
   542.2 3158.81   551.7 3161.36   558.6 3164.05     585 3167.36  622.08 3174.87
   680.5 3183.32   726.7 3185.95   802.4 3198.25   861.7 3211.53   933.1 3222.38
#Mann= 5 ,-1 , 0
       0      .1       0  375.07    .055       0   534.6    .045       0
   551.7    .055       0  622.08      .1       0
#XS Ineff= 2 , 0
          475.79 3171.32
Permanent Ineff=
       F       F
Bank Sta=534.6,551.7
XS Rating Curve= 0 ,0
Exp/Cntr=0.3,0.1

Type RM Length L Ch R = 1 ,16809   ,247.4,252.8,243.6
XS GIS Cut Line= 2
2067939.68812027386018.595335431 2066990.8257206385945.689623529
#Sta/Elev= 30
       0 3216.47    21.1 3209.39    44.1 3207.31      77 3196.75   123.1 3188.53
     179 3173.86  222.81 3172.78   267.8 3169.48   287.6 3171.01     304  3168.2
   333.7 3169.17   382.2 3164.82  436.17 3164.07   452.1 3165.84   463.6 3159.94
   468.6 3157.83   504.5 3157.47   517.9  3160.3   528.9 3163.01   557.4 3164.97
   679.2 3168.77   721.9 3172.56   764.7 3173.63   782.5 3181.78     847 3193.51
   873.3 3195.04   889.8 3192.39   902.9 3192.78   925.9 3204.93   951.7 3212.17
#Mann= 5 ,-1 , 0
       0      .1       0  222.81    .055       0  436.17      .1       0
   463.6    .045       0   517.9      .1       0
Bank Sta=463.6,517.9
XS Rating Curve= 0 ,0
Exp/Cntr=0.3,0.1

Type RM Length L Ch R = 1 ,16556   ,316.4,322.6,324.7
XS GIS Cut Line= 2
2067892.21492151385747.4785265042066973.82058054385724.627482475
#Sta/Elev= 30
       0  3220.7    19.5  3214.4    35.9 3206.02    45.7 3202.64    58.8 3201.42
    81.8 3201.18   114.6 3195.23   130.8  3189.7   137.6 3188.43   167.1 3187.66
   189.6 3183.38   222.9 3177.36   262.3 3174.45   285.3 3170.38   360.8 3166.03
   373.9 3163.07  412.47 3165.24   419.8 3166.55   431.4 3160.21   442.8 3157.61
   465.8 3157.75   475.6  3159.4   498.6 3161.12   554.4 3162.88   633.2 3169.34
     771 3186.21   813.7 3190.43   869.5 3202.94   889.2  3204.2   918.7 3209.39
#Mann= 5 ,-1 , 0
       0      .1       0   189.6    .055       0  412.47      .1       0
   431.4    .045       0   475.6      .1       0
Bank Sta=431.4,475.6
XS Rating Curve= 0 ,0
Exp/Cntr=0.3,0.1

Type RM Length L Ch R = 1 ,16234   ,349.1,338.8,323.1
XS GIS Cut Line= 3
     2067866.799      385453.205     2067406.194      385422.938
     2066952.213      385400.857
#Sta/Elev= 30
       0 3221.94    20.3 3217.31    49.9 3215.86  185.82 3193.86   201.2 3190.73
   214.3 3186.26   250.5 3183.92   266.9 3180.34   284.4 3174.16   306.4 3168.69
   352.4 3161.04   362.3 3160.32   401.7 3162.16   411.6    3164  419.15 3159.84
   420.3 3159.19   424.7 3157.74   436.7 3157.49   490.5 3158.89   500.3  3161.2
   651.4 3170.98   671.1  3173.3   702.5 3181.86   713.8    3183   727.6 3186.73
   799.2 3201.15   832.1 3206.05   881.4    3217   897.8  3222.3   916.1  3230.5
#Mann= 5 ,-1 , 0
       0      .1       0  185.82    .055       0  419.15      .1       0
   420.3    .045       0   490.5      .1       0
#XS Ineff= 2 , 0
          410.49  3165.6
Permanent Ineff=
       F       F
Bank Sta=420.3,490.5
XS Rating Curve= 0 ,0
Exp/Cntr=0.3,0.1

Type RM Length L Ch R = 1 ,15895   ,311.2,315,317
XS GIS Cut Line= 2
     2067761.833      384904.621     2066939.529       385317.18
#Sta/Elev= 30
       0 3211.28    41.1 3203.61   118.2 3194.16   137.9 3188.48   154.9 3187.88
   169.5 3182.18   187.9 3177.61   206.3 3177.93  222.23 3174.06     287  3168.4
   349.4 3166.15   367.8 3164.07   386.1 3158.59   414.1 3160.36   430.2 3162.21
   448.5 3157.11   455.9 3154.61   470.5 3155.02   479.2 3157.08   486.5 3160.41
   496.4 3162.17     588 3167.16   602.7  3170.9   624.7 3179.36     650 3184.11
   699.2 3190.43   779.8 3204.47   853.2 3213.67     900  3224.9     920 3232.16
#Mann= 5 ,-1 , 0
       0      .1       0  222.23    .055       0   414.1      .1       0
   448.5    .045       0   479.2      .1       0
#XS Ineff= 2 , 0
          428.17 3164.93
Permanent Ineff=
       F       F
Bank Sta=448.5,479.2
XS Rating Curve= 0 ,0
Exp/Cntr=0.3,0.1

Type RM Length L Ch R = 1 ,15580   ,259.2,263.1,266.1
XS GIS Cut Line= 2
2067684.62104533384717.8515902632066811.68698243384934.271531066
#Sta/Elev= 30
       0 3202.06    32.6  3198.5    60.8 3197.01   147.6 3183.44   154.3  3181.2
   167.8 3181.22  192.06 3177.87   313.2    3164   353.3 3163.21  370.94 3161.17
   384.2 3155.96   435.4  3157.1   446.9 3154.67   458.9 3152.14   488.7 3154.84
   496.9 3156.04   529.5 3165.47   539.7 3167.29   576.8 3167.87   593.7 3170.33
   600.5 3170.32   617.4 3174.52     658 3179.59   701.9  3187.3   756.9 3199.26
   797.5 3210.31   813.5 3212.63   833.7 3217.22   871.4 3227.81   899.4  3237.1
#Mann= 5 ,-1 , 0
       0      .1       0  192.06    .055       0  370.94      .1       0
   446.9    .045       0   488.7      .1       0
#XS Ineff= 2 , 0
          425.39 3160.91
Permanent Ineff=
       F       F
Bank Sta=446.9,488.7
XS Rating Curve= 0 ,0
Exp/Cntr=0.3,0.1

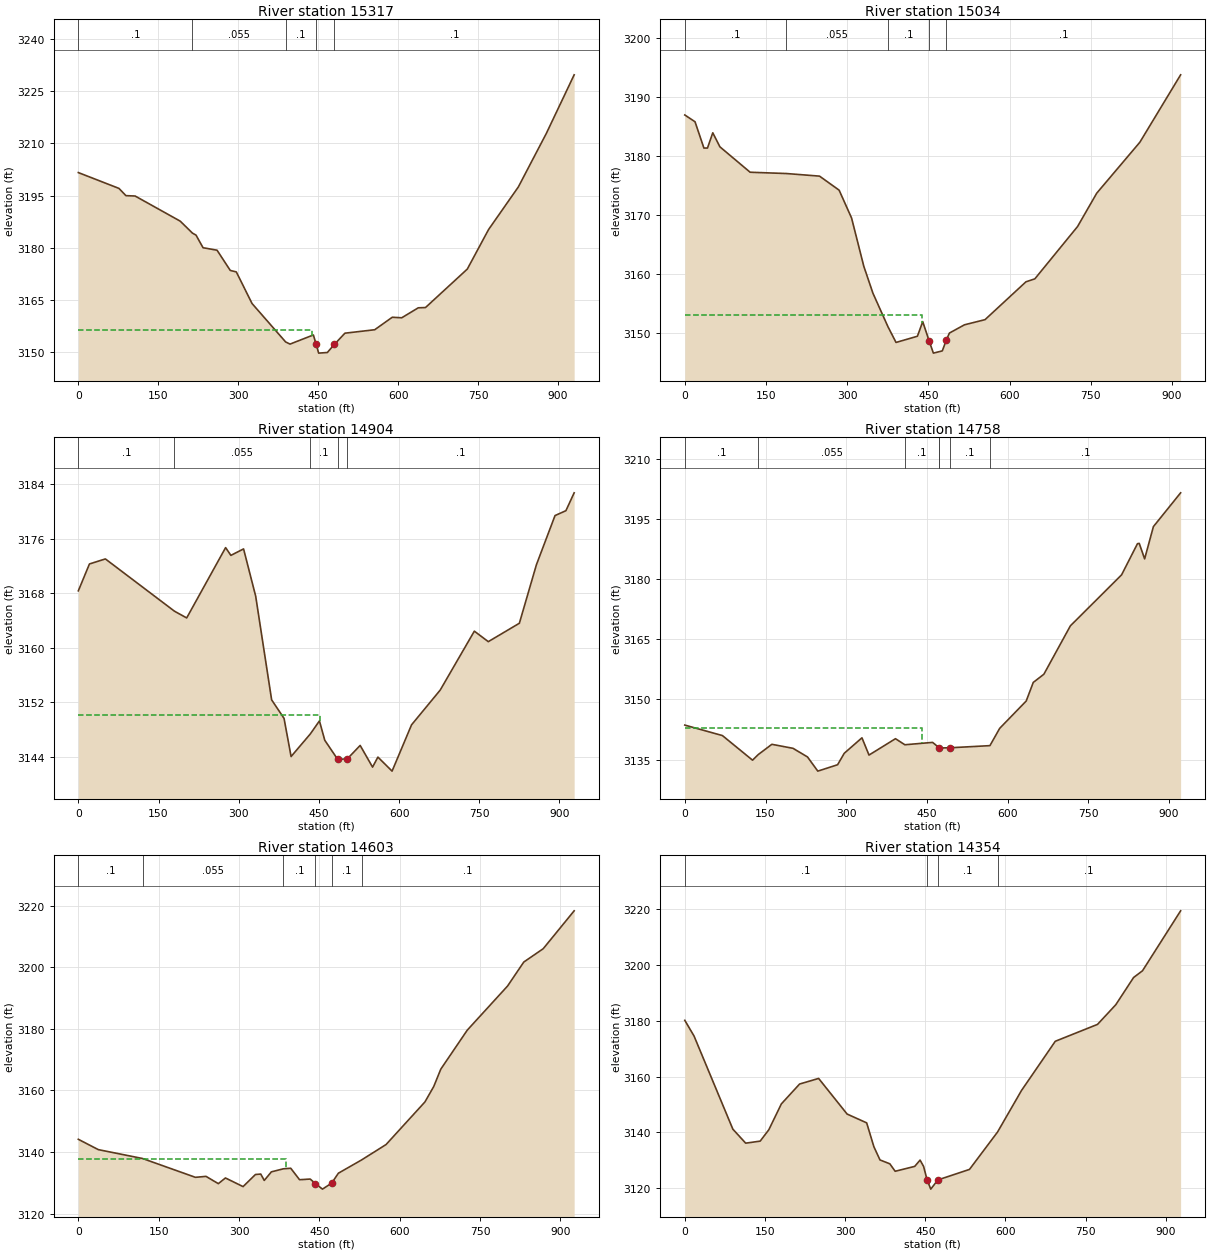
Type RM Length L Ch R = 1 ,15317   ,284,283.1,282.8
XS GIS Cut Line= 2
2067656.81289652384547.3755475092066728.26253598384604.200895094
#Sta/Elev= 30
       0 3201.61    76.2 3197.07    89.3 3194.99   106.6 3194.88   191.2 3187.67
  214.11 3184.24   220.8 3183.67     234 3180.05   260.3 3179.33   285.1 3173.53
   296.4 3173.11     326 3164.03  388.89 3153.03   397.2  3152.4     441 3155.02
   446.2 3152.35   450.9 3149.81   467.2 3149.99   480.5 3152.32   500.2 3155.53
   556.1 3156.52     589  3160.1   606.8 3159.95   637.8 3162.81   651.4 3162.89
   729.8 3173.92   769.7 3185.26   825.6 3197.49   878.2 3212.87   930.3 3229.65
#Mann= 5 ,-1 , 0
       0      .1       0  214.11    .055       0  388.89      .1       0
   446.2    .045       0   480.5      .1       0
#XS Ineff= 2 , 0
          438.24 3156.46
Permanent Ineff=
       F       F
Bank Sta=446.2,480.5
XS Rating Curve= 0 ,0
Exp/Cntr=0.3,0.1

Type RM Length L Ch R = 1 ,15034   ,128.4,130.3,133.5
XS GIS Cut Line= 3
     2067579.902       384281.68     2067118.789      384308.584
     2066665.645      384337.036
#Sta/Elev= 30
       0 3187.01    18.9 3185.86    35.3 3181.41    41.9 3181.41    51.7 3183.99
    64.9 3181.61   120.7 3177.31  187.82 3177.09   248.9 3176.65   285.1 3174.27
   308.1 3169.55   330.6  3161.4   347.5 3156.83  375.31 3151.14   390.2 3148.48
   429.7 3149.53   439.5    3152   451.7 3148.64   459.2 3146.67   475.7 3147.05
   483.2 3148.91   488.8 3150.07   516.7 3151.47   554.6 3152.34   630.2 3158.75
   646.6 3159.25   725.5 3168.11     761 3173.77   840.6 3182.39   915.9 3193.81
#Mann= 5 ,-1 , 0
       0      .1       0  187.82    .055       0  375.31      .1       0
   451.7    .045       0   483.2      .1       0
#XS Ineff= 2 , 0
          438.83 3153.07
Permanent Ineff=
       F       F
Bank Sta=451.7,483.2
XS Rating Curve= 0 ,0
Exp/Cntr=0.3,0.1

Type RM Length L Ch R = 1 ,14904   ,146.8,145.7,142
XS GIS Cut Line= 3
2067607.95223347384173.9576159792067331.07979524384209.020064489
2066689.07427252384118.341318343
#Sta/Elev= 30
       0 3168.38    20.8 3172.32    50.6 3173.06  179.85 3165.39   202.7  3164.4
   275.5 3174.72   285.4 3173.58   309.1 3174.53   331.8 3167.58   361.6 3152.38
   384.8 3149.66     398 3144.06  433.99 3147.38     451 3149.29     461 3146.45
   485.3 3143.63   503.3 3143.73   527.2 3145.69   550.4 3142.51   560.4 3143.98
   586.9 3141.92   623.3 3148.71   676.9 3153.81   740.8 3162.46   766.9 3160.92
     825 3163.62   856.9 3172.21   891.7 3179.42   912.1 3180.14   927.5 3182.76
#Mann= 5 ,-1 , 0
       0      .1       0  179.85    .055       0  433.99      .1       0
   485.3    .045       0   503.3      .1       0
#XS Ineff= 2 , 0
           451.2 3150.17
Permanent Ineff=
       F       F
Bank Sta=485.3,503.3
XS Rating Curve= 0 ,0
Exp/Cntr=0.3,0.1

Type RM Length L Ch R = 1 ,14758   ,152.1,154.5,155.6
XS GIS Cut Line= 2
2067621.11054663384058.725142455 2066700.1369672384025.603215522
#Sta/Elev= 30
       0 3143.58    69.9 3140.97   125.9 3134.84   136.5 3136.23   161.8 3138.79
   201.2 3137.79   228.1 3135.64   247.2 3132.11     284  3133.7   296.4 3136.56
   329.3 3140.41   342.4 3136.11   391.6 3140.19  409.01 3138.68   460.6 3139.27
  473.07  3137.9   473.3 3137.88   493.1 3137.93  567.15 3138.46   585.3 3142.77
   634.6 3149.58   647.7 3154.21   667.4 3156.25   716.7 3168.31   811.9 3181.02
   841.4 3188.78   844.7 3188.85   854.7 3184.99     871 3193.03   921.6 3201.45
#Mann= 7 ,-1 , 0
       0      .1       0   136.5    .055       0  409.01      .1       0
  473.07      .1       0   473.3    .045       0   493.1      .1       0
  567.15      .1       0
#XS Ineff= 2 , 0
          440.24 3142.85
Permanent Ineff=
       F       F
Bank Sta=473.3,493.1
XS Rating Curve= 0 ,0
Exp/Cntr=0.3,0.1

Type RM Length L Ch R = 1 ,14603   ,251.4,249.2,245.8
XS GIS Cut Line= 2
 2067650.7368892383945.1225824082066729.18692786383856.003510695
#Sta/Elev= 30
       0 3144.15    37.3  3140.8  120.11 3137.91   218.6 3131.81   238.4 3132.12
   261.4 3129.76   274.7  3131.6   307.6  3128.8   330.7 3132.72   340.6 3132.87
   347.2  3130.8   360.4 3133.58  382.47 3134.56   396.6 3134.76   413.1 3131.03
   432.9 3131.25   442.8 3129.76   455.9 3127.98     473 3129.93   485.6 3133.15
  528.78 3137.44   574.6 3142.45   647.1 3156.26   663.6 3161.27   676.8 3166.92
   726.2 3179.57   801.5  3193.9   831.7 3201.67     868    3206   925.8  3218.3
#Mann= 6 ,-1 , 0
       0      .1       0  120.11    .055       0  382.47      .1       0
   442.8    .045       0     473      .1       0  528.78      .1       0
#XS Ineff= 2 , 0
           387.4 3137.71
Permanent Ineff=
       F       F
Bank Sta=442.8,473
XS Rating Curve= 0 ,0
Exp/Cntr=0.3,0.1

Type RM Length L Ch R = 1 ,14354   ,250.3,249.9,244.6
XS GIS Cut Line= 2
2067666.70962389383583.6558814412066752.66786274383742.041424711
#Sta/Elev= 30
       0 3180.14    17.3 3174.51    89.9 3141.15   113.9 3136.13     141 3136.85
   157.2 3140.93   180.7  3150.2   214.8 3157.31   250.4 3159.32   303.7 3146.55
   340.3  3143.4   353.8 3134.84   365.2 3130.12   383.6 3128.73   393.6 3126.06
   430.2 3127.81   440.2 3130.06   446.8  3127.8   453.2 3123.08   460.2 3119.66
   473.5 3122.96   532.6 3126.72  585.07 3140.09     630    3155   693.2 3172.63
   772.2 3178.68   806.4 3185.72   839.7 3195.47   856.4 3197.89   927.7 3219.36
#Mann= 4 ,-1 , 0
       0      .1       0   453.2    .045       0   473.5      .1       0
  585.07      .1       0
Bank Sta=453.2,473.5
XS Rating Curve= 0 ,0
Exp/Cntr=0.3,0.1

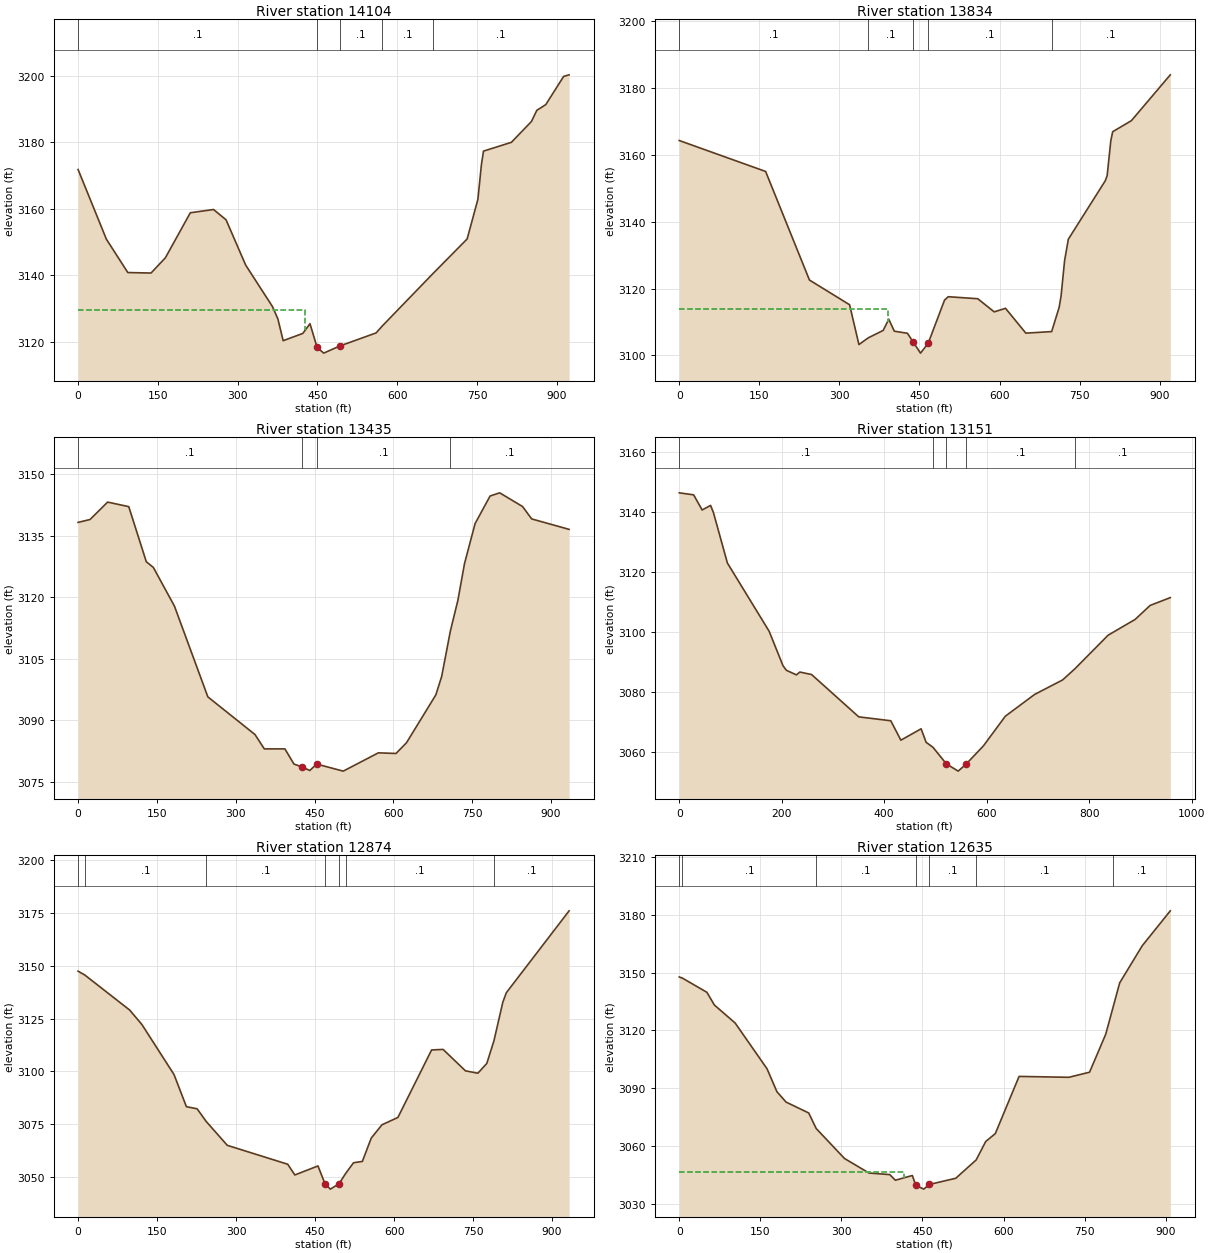
Type RM Length L Ch R = 1 ,14104   ,272.1,270.4,271
XS GIS Cut Line= 2
 2067636.0192498383327.0880702642066734.05589763383523.933492398
#Sta/Elev= 30
       0 3171.83    53.2 3150.87    93.5 3140.83   137.1 3140.68   164.1 3145.26
     211 3158.82   254.7  3159.8   278.2  3156.7   315.1 3143.07   365.5 3130.58
   375.6 3126.89   385.6 3120.32   422.6 3122.52     436 3125.44   449.4 3118.28
   461.8 3116.58   492.1 3118.73   560.3 3122.66  572.32 3124.81  666.79 3140.45
   731.5 3150.94   751.7 3162.88   758.4 3173.39   762.2 3177.37   814.6 3180.01
   852.4 3186.29   862.5 3189.65   879.3 3191.36   912.9 3199.85   923.2 3200.33
#Mann= 5 ,-1 , 0
       0      .1       0   449.4    .045       0   492.1      .1       0
  572.32      .1       0  666.79      .1       0
#XS Ineff= 2 , 0
          427.25 3129.54
Permanent Ineff=
       F       F
Bank Sta=449.4,492.1
XS Rating Curve= 0 ,0
Exp/Cntr=0.3,0.1

Type RM Length L Ch R = 1 ,13834   ,396,399.1,400.2
XS GIS Cut Line= 3
     2067581.659      383003.872     2067156.747      383160.392
     2066714.039      383309.652
#Sta/Elev= 30
       0 3164.26   161.8 3155.01   243.9 3122.54   319.1 3115.15   336.6 3103.24
  353.81 3105.22   382.1 3107.48   392.5 3110.82     403 3107.23   427.5 3106.62
   438.5 3103.94     452 3100.68   466.4 3103.64     497 3116.54   503.9 3117.55
   559.3 3116.95     590 3113.02   611.3 3114.08   649.3 3106.66   697.7 3107.12
   711.7 3114.33   715.4 3117.81     722  3128.4     729 3134.76   798.2 3152.23
   801.7 3153.77   808.6 3164.26   812.1  3166.9   847.1  3170.2     920 3183.91
#Mann= 5 ,-1 , 0
       0      .1       0  353.81      .1       0   438.5    .045       0
   466.4      .1       0   697.7      .1       0
#XS Ineff= 2 , 0
          390.18    3114
Permanent Ineff=
       F       F
Bank Sta=438.5,466.4
XS Rating Curve= 0 ,0
Exp/Cntr=0.3,0.1

Type RM Length L Ch R = 1 ,13435   ,275.3,284.2,286.3
XS GIS Cut Line= 2
2067514.49979091382695.2699835952066598.29489622382878.014822698
#Sta/Elev= 30
       0  3138.2    22.8 3138.91    56.2 3143.15    96.4 3142.04   129.8 3128.61
   143.2 3127.22   183.3 3117.81   246.9 3095.67   336.6 3086.49   354.4 3082.99
   393.5 3082.99   410.8 3079.29   426.1 3078.59   440.9 3077.73     454 3079.29
   504.5 3077.57   571.4 3082.03   604.9 3081.87   624.9 3084.49   680.7 3096.15
   691.8 3100.64  708.54 3111.83   722.6 3119.17   735.3 3128.18   755.4 3137.91
   783.9 3144.63   802.2 3145.41   845.7 3142.07   863.1 3139.05   934.3  3136.5
#Mann= 4 ,-1 , 0
       0      .1       0   426.1    .045       0     454      .1       0
  708.54      .1       0
Bank Sta=426.1,454
XS Rating Curve= 0 ,0
Exp/Cntr=0.3,0.1

Type RM Length L Ch R = 1 ,13151   ,269.2,276.7,280.3
XS GIS Cut Line= 2
2067451.42486211382530.2540050462066494.94544776382590.101977503
#Sta/Elev= 30
       0 3146.51    28.1 3145.83    44.6  3140.8    61.1 3142.32    66.7 3139.92
    93.9 3123.13   175.4 3100.39   202.4 3088.93     209 3087.39   228.7 3085.86
   235.3  3086.8   258.3 3085.96   350.3 3071.87   412.8 3070.57   432.5  3064.1
     472 3067.89   481.8 3063.38   495.1 3061.74   521.3 3056.21   544.3 3053.79
   560.4 3056.23   593.6  3062.2   636.3 3072.08   693.4 3079.33   748.1 3084.17
  772.03 3087.87   836.9 3099.07   889.5 3104.31     919    3109   958.3 3111.59
#Mann= 5 ,-1 , 0
       0      .1       0   495.1      .1       0   521.3    .045       0
   560.4      .1       0  772.03      .1       0
Bank Sta=521.3,560.4
XS Rating Curve= 0 ,0
Exp/Cntr=0.3,0.1

Type RM Length L Ch R = 1 ,12874   ,236.6,238.4,239.6
XS GIS Cut Line= 2
2067423.13309332382410.5580601332066516.70834684382191.840924427
#Sta/Elev= 30
       0 3147.45   12.77 3145.63    97.9 3129.07   121.3 3122.17   182.1 3098.58
   205.7 3083.34     226 3082.35  243.27 3076.35   283.3 3065.06   398.1 3056.11
   411.6 3051.04   455.5 3055.31     469  3046.8   479.1 3044.34   495.7 3046.93
  507.81 3051.66     523 3056.82   539.8 3057.45   556.7  3068.5     577 3074.77
   607.3 3078.25   671.3 3110.18   693.1 3110.44   735.6  3100.3   759.2 3099.18
   776.1 3103.81  789.64  3114.5   806.5 3132.75   813.2 3137.26   932.4    3176
#Mann= 7 ,-1 , 0
       0      .1       0   12.77      .1       0  243.27      .1       0
     469    .045       0   495.7      .1       0  507.81      .1       0
  789.64      .1       0
Bank Sta=469,495.7
XS Rating Curve= 0 ,0
Exp/Cntr=0.3,0.1

Type RM Length L Ch R = 1 ,12635   ,305.5,301.6,293.7
XS GIS Cut Line= 2
2067477.89915963382235.889636711     2066623.368      381927.172
#Sta/Elev= 30
       0 3147.71    5.93 3147.09    51.1 3139.77      65 3133.18   103.4 3123.88
   162.4 3100.19   180.7 3088.33   197.6 3082.96   239.5 3077.32  253.36 3069.28
   305.7 3053.77   351.1 3046.24   389.5 3045.43   399.9 3042.52   431.3 3044.96
   437.6 3039.93   452.3 3037.91   462.7 3040.32   511.6 3043.53   549.4 3053.02
     567 3062.53   584.8 3066.65   628.8 3096.24   720.9 3095.78   759.2 3098.42
   789.1 3118.05  803.21 3132.55     815 3144.68   856.8 3163.91   908.6 3181.93
#Mann= 7 ,-1 , 0
       0      .1       0    5.93      .1       0  253.36      .1       0
   437.6    .045       0   462.7      .1       0   549.4      .1       0
  803.21      .1       0
#XS Ineff= 2 , 0
          416.04 3046.82
Permanent Ineff=
       F       F
Bank Sta=437.6,462.7
XS Rating Curve= 0 ,0
Exp/Cntr=0.3,0.1

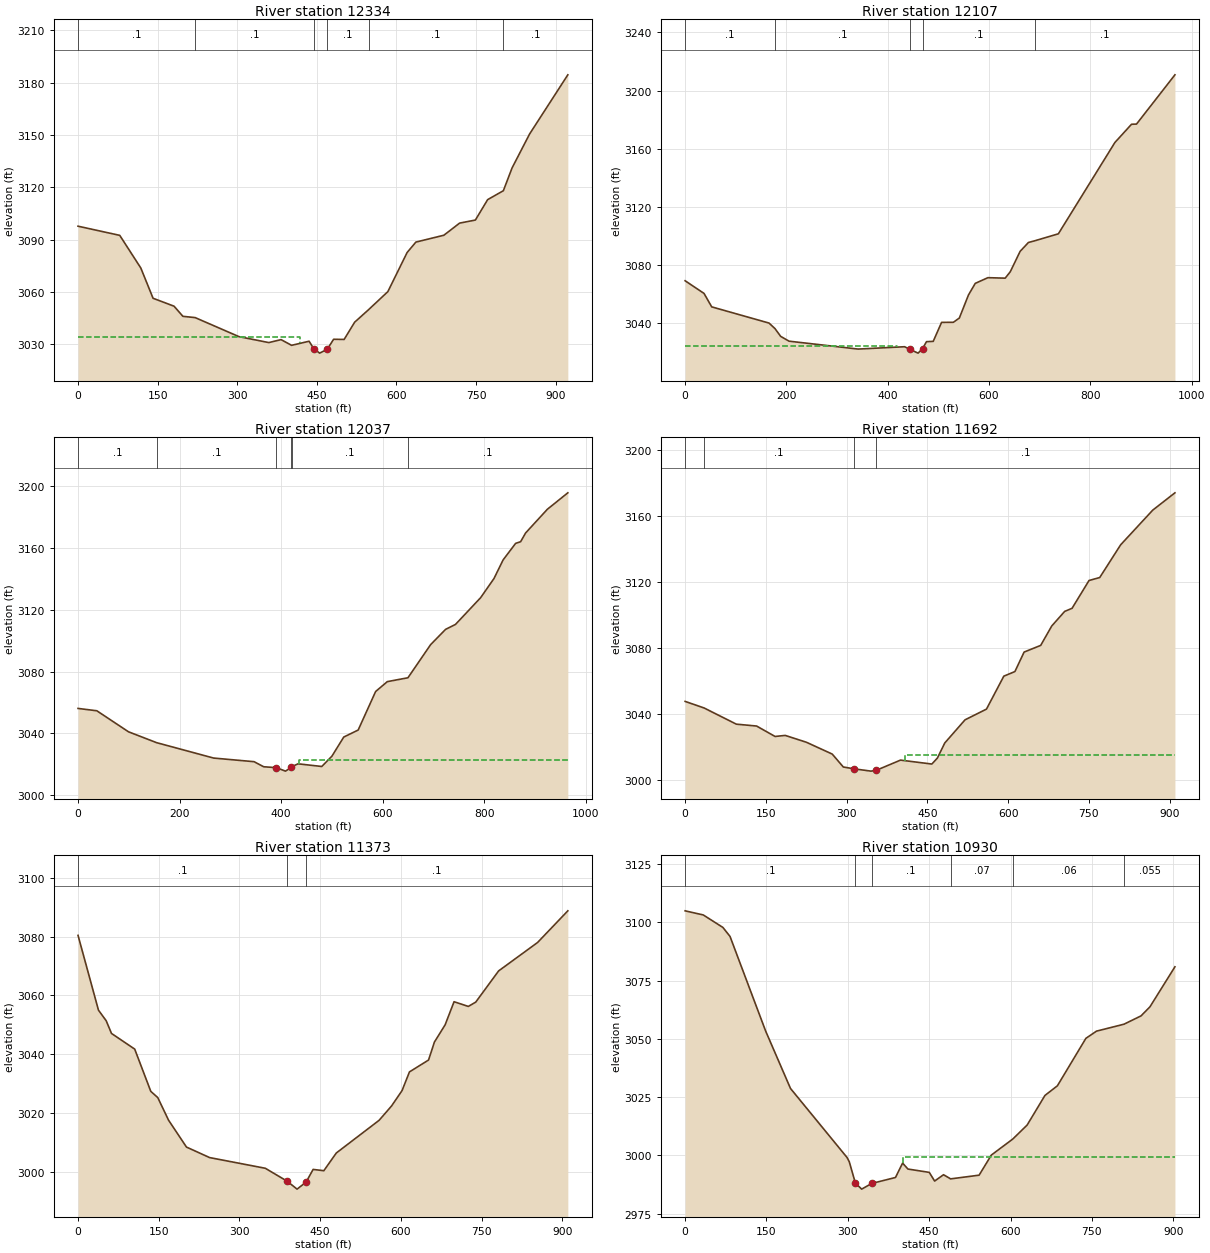
Type RM Length L Ch R = 1 ,12334   ,224,226.4,229.4
XS GIS Cut Line= 3
     2067553.857      381736.726     2067103.258      381790.114
     2066636.381        381836.3
#Sta/Elev= 30
       0 3097.64    78.6 3092.38   118.3 3073.66   141.4  3056.3   180.9 3051.76
   197.6 3045.95   220.7 3045.21   303.3 3034.29   359.4 3030.89   382.6 3032.58
   402.4 3029.31   435.4 3031.66   444.1 3027.38   455.3 3024.84   469.5 3027.04
   481.6 3032.79   501.4 3032.69   521.2 3042.57   547.6  3049.8   583.8 3060.12
   620.1 3082.55   636.6 3088.52   689.3 3092.45     719 3099.41   748.7 3101.16
   771.8 3112.86   801.4 3117.98   817.9  3131.1   850.9 3150.54   922.9 3184.45
#Mann= 6 ,-1 , 0
       0      .1       0   220.7      .1       0   444.1    .045       0
   469.5      .1       0   547.6      .1       0   801.4      .1       0
#XS Ineff= 2 , 0
          418.36 3033.82
Permanent Ineff=
       F       F
Bank Sta=444.1,469.5
XS Rating Curve= 0 ,0
Exp/Cntr=0.5,0.3

Type RM Length L Ch R = 1 ,12107   ,72.3,70.8,72.5
XS GIS Cut Line= 4
2067512.94446949381577.4926617722067222.16212056381601.913835608
2066931.94770591381559.3187649642066550.29587294381547.392145184
#Sta/Elev= 30
       0 3069.13    37.3 3060.42    52.5 3051.17   165.7 3040.02  177.36 3036.23
   188.7 3030.86   205.2 3027.57   341.5 3022.14   433.4 3023.75   443.3 3021.99
   459.9 3019.35   468.7 3022.39   476.5 3027.24   489.8 3027.44   506.3  3040.5
   529.6 3040.56   541.4 3043.51   559.4 3059.35   572.8 3067.34   597.8 3071.25
   631.9 3070.92   641.9  3075.3   661.4 3089.37   677.8 3095.46   690.8 3096.68
   736.9 3101.43   848.5 3164.24   881.3 3176.78   891.2 3176.92     967 3210.79
#Mann= 5 ,-1 , 0
       0      .1       0  177.36      .1       0   443.3    .045       0
   468.7      .1       0   690.8      .1       0
#XS Ineff= 2 , 0
          417.38    3024     473            3024
Permanent Ineff=
       F       F
Bank Sta=443.3,468.7
XS Rating Curve= 0 ,0
Exp/Cntr=0.5,0.3

Type RM Length L Ch R = 1 ,12037   ,346,344.4,336.7
XS GIS Cut Line= 4
2067489.72054119381517.659380837 2067203.1998201381533.240568086
2066942.64774442381486.4970063372066529.74628231381477.840791198
#Sta/Elev= 30
       0 3056.12      37  3054.6    99.4 3040.98  154.64 3033.96     267 3023.98
   346.7 3021.63   365.6 3018.35   390.1 3017.78   408.6 3015.52     420 3017.93
  421.28 3018.42   433.3 3020.26     480 3018.52     500 3025.19   523.3 3037.58
   551.7 3042.12   586.1 3067.08   609.1 3073.46  649.73 3075.97   694.4 3097.42
   723.9 3107.32   743.4 3110.51   792.9 3127.83   819.1 3140.18   837.2  3152.3
   861.8 3162.98   871.6 3164.04   881.5 3169.73   924.4 3185.09   964.6  3195.7
#Mann= 6 ,-1 , 0
       0      .1       0  154.64      .1       0   390.1    .045       0
     420      .1       0  421.28      .1       0  649.73      .1       0
#XS Ineff= 2 , 0
                           434.3         3022.97
Permanent Ineff=
       F       F
Bank Sta=390.1,420
XS Rating Curve= 0 ,0
Exp/Cntr=0.5,0.3

Type RM Length L Ch R = 1 ,11692   ,314.9,319.5,318.2
XS GIS Cut Line= 3
     2067363.367      381097.013     2066927.859      381228.762
     2066492.351      381360.509
#Sta/Elev= 30
       0 3047.66   35.24 3043.69    95.1  3033.9   132.8 3032.76   167.1 3026.45
     186 3027.09   225.3 3022.95   273.3  3015.8   293.9 3007.98   314.4 3006.84
   345.3 3005.48   355.4 3006.01   400.1 3012.14   458.4 3009.77   468.7 3013.39
   482.4 3022.51   520.1 3036.53   559.9 3043.01   592.1 3062.94   612.7 3065.72
   629.8 3077.52   660.6 3081.54   681.2 3093.32   705.2 3102.12   718.9 3103.99
   750.4 3120.81   770.3 3122.61   809.1 3142.38   868.8 3163.38     910 3173.85
#Mann= 4 ,-1 , 0
       0      .1       0   35.24      .1       0   314.4    .045       0
   355.4      .1       0
#XS Ineff= 2 , 0
                          408.05         3015.08
Permanent Ineff=
       F       F
Bank Sta=314.4,355.4
XS Rating Curve= 0 ,0
Exp/Cntr=0.3,0.1

Type RM Length L Ch R = 1 ,11373   ,437.4,442.5,442.4
XS GIS Cut Line= 2
     2067301.155       380867.57     2066400.424       380997.53
#Sta/Elev= 30
       0 3080.47      38 3054.99    52.3  3051.4    62.2 3047.07   105.3 3041.74
   135.2 3027.35   148.1 3025.25   168.3 3017.51   201.5 3008.38   244.5  3004.8
     348 3001.16   388.5 2996.77     407 2994.06   423.9 2996.48   436.8 3000.77
   456.7 3000.33   479.9 3006.36   559.5  3017.5   582.7 3022.41   602.1 3027.62
   615.8 3033.97   651.3 3038.02   662.2 3044.13   682.1 3050.01   698.7 3057.87
   725.2 3056.27     739 3057.74   781.5 3068.36   853.9 3078.04   910.1 3088.82
#Mann= 3 ,-1 , 0
       0      .1       0   388.5    .045       0   423.9      .1       0
Bank Sta=388.5,423.9
XS Rating Curve= 0 ,0
Exp/Cntr=0.3,0.1

Type RM Length L Ch R = 1 ,10930   ,152.8,155.8,162
XS GIS Cut Line= 2
2067282.93990468380495.4546854292066379.77959306380505.247990013
#Sta/Elev= 30
       0 3104.89    33.5 3103.12    69.6 3097.78    82.8 3093.91   148.4 3053.39
   194.3 3028.73   298.6 2999.12   302.6 2997.36     314 2988.12   325.6 2985.56
     344 2987.99   387.9 2990.55     401 2996.72   410.9 2994.17   450.2 2992.74
   460.1 2989.02   476.5 2991.74  489.57 2989.96   542.1 2991.54   564.7 3000.17
  604.24 3007.04   630.7 3013.04   663.5 3025.73   686.5 3029.87     739 3050.21
   758.6  3053.3  809.29 3056.28   840.7 3059.84   857.1 3063.71   903.2 3080.89
#Mann= 6 ,-1 , 0
       0      .1       0     314    .045       0     344      .1       0
  489.57     .07       0  604.24     .06       0  809.29    .055       0
#XS Ineff= 2 , 0
                          401.05         2999.48
Permanent Ineff=
       F       F
Bank Sta=314,344
XS Rating Curve= 0 ,0
Exp/Cntr=0.3,0.1

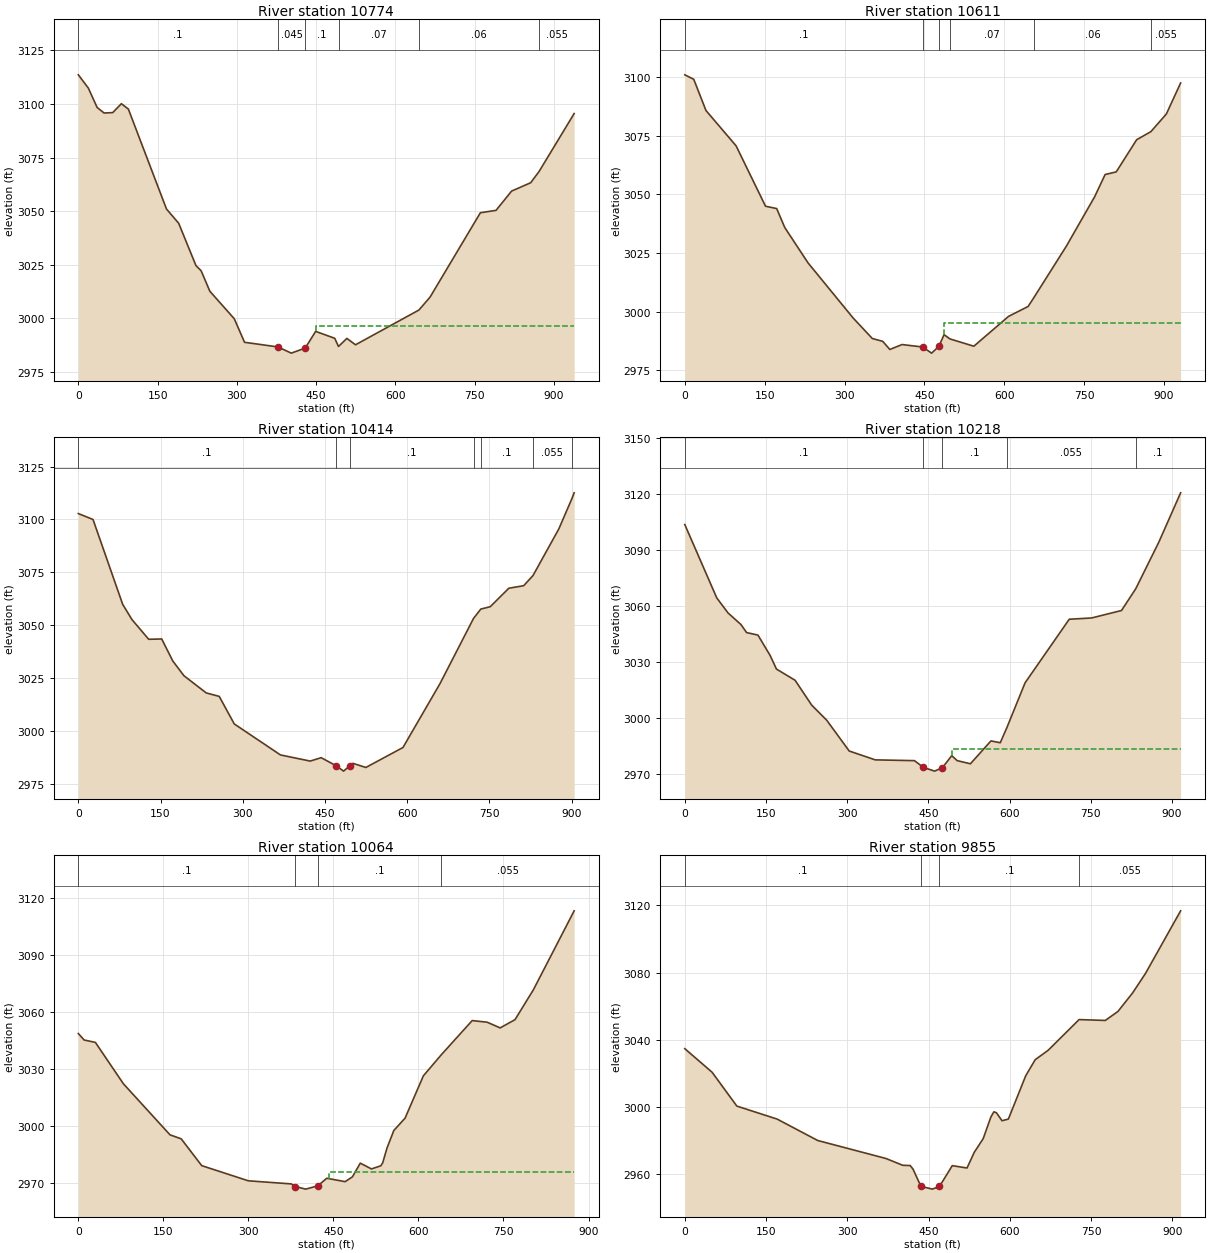
Type RM Length L Ch R = 1 ,10774   ,162.8,162.9,159.3
XS GIS Cut Line= 2
 2067317.7605432380363.7891460242066379.77959306380332.232942365
#Sta/Elev= 30
       0 3113.64    18.9 3107.47    35.6  3098.4    48.7 3095.81    65.1    3096
    81.5 3100.16    94.7 3097.66   166.9 3050.97   189.9 3044.35   222.7 3024.55
   232.5 3022.12   248.9  3012.6   295.2 2999.74   314.6 2988.75   377.7 2986.59
   403.1 2983.69   429.5 2986.06   449.2 2993.84   485.3 2990.62  492.47  2986.8
   508.3 2990.57   524.7 2987.59  644.67 3003.81   665.8 3009.86     761 3049.24
   790.6 3050.35   820.1 3059.35   856.2 3063.25  872.11  3068.5   938.5 3095.56
#Mann= 6 ,-1 , 0
       0      .1       0   377.7    .045       0   429.5      .1       0
  492.47     .07       0  644.67     .06       0  872.11    .055       0
#XS Ineff= 2 , 0
                          449.36         2996.52
Permanent Ineff=
       F       F
Bank Sta=377.7,429.5
XS Rating Curve= 0 ,0
Exp/Cntr=0.3,0.1

Type RM Length L Ch R = 1 ,10611   ,194.1,197.4,199.3
XS GIS Cut Line= 2
2067354.75747163380224.5065919432066425.48168112380166.834909394
#Sta/Elev= 30
       0 3100.84    16.8 3098.94    39.8 3085.64    96.3 3070.63   151.6 3044.92
   172.6 3043.91   187.7 3035.86   231.4 3020.81   315.9  2997.4   352.1 2988.62
   371.8 2987.39     385 2983.95     408 2986.04   446.4    2985   463.5 2982.39
     477 2985.24   486.9 2990.24  497.97 2988.43   542.8 2985.33   607.9 2998.02
   644.7 3002.25  656.54 3006.38   716.6 3027.94   769.6 3048.92   789.3  3058.4
   810.2 3059.53   848.5 3073.21  875.27 3076.66   904.3 3084.17   931.1 3097.37
#Mann= 6 ,-1 , 0
       0      .1       0   446.4    .045       0     477      .1       0
  497.97     .07       0  656.54     .06       0  875.27    .055       0
#XS Ineff= 2 , 0
                          486.56         2995.11
Permanent Ineff=
       F       F
Bank Sta=446.4,477
XS Rating Curve= 0 ,0
Exp/Cntr=0.3,0.1

Type RM Length L Ch R = 1 ,10414   ,195.5,196,195.6
XS GIS Cut Line= 2
2067383.59061414380125.2914516472066507.28241492379900.871059164
#Sta/Elev= 30
       0  3102.8    26.8    3100    80.9 3059.87    97.9 3052.63   128.4 3043.32
   152.1 3043.47   172.4 3033.03   192.7 3026.08   233.3 3017.96   257.1  3016.3
   284.5 3003.28   368.8 2988.61     423  2985.7     443 2987.31     470 2983.55
     484 2980.95   495.1 2983.48   500.9 2984.64   524.6 2982.68   592.3 2992.13
   660.1 3022.47  721.07 3053.22  734.31 3057.62   751.5 3058.73   785.4 3067.47
   812.5 3068.67  829.45 3073.45   876.8 3095.61  900.07 3109.63   904.6 3112.61
#Mann= 7 ,-1 , 0
       0      .1       0     470    .045       0   495.1      .1       0
  721.07    .055       0  734.31      .1       0  829.45    .055       0
  900.07      .1       0
Bank Sta=470,495.1
XS Rating Curve= 0 ,0
Exp/Cntr=0.3,0.1

Type RM Length L Ch R = 1 ,10218   ,158,153.8,148.9
XS GIS Cut Line= 2
     2067433.586      379968.574     2066561.356      379689.678
#Sta/Elev= 30
       0 3103.61      59 3064.32    79.7 3056.28   103.8    3050   114.1 3045.72
   135.1 3044.37   157.7  3033.4   169.3 3026.15   203.7 3020.16   234.3 3006.86
   262.3 2998.68   303.6 2982.25   351.8 2977.49   424.2 2977.08   440.5 2973.48
   461.4 2971.46   475.8 2973.32     493 2979.75   503.1 2977.08   527.5  2975.4
   565.4 2987.66   582.6 2986.67  595.04 2994.92   628.4 3018.77     710 3052.86
   751.4 3053.55   806.5 3057.55  832.82  3069.2   875.4 3094.14   915.7 3120.61
#Mann= 5 ,-1 , 0
       0      .1       0   440.5    .045       0   475.8      .1       0
  595.04    .055       0  832.82      .1       0
#XS Ineff= 2 , 0
                          493.28         2983.08
Permanent Ineff=
       F       F
Bank Sta=440.5,475.8
XS Rating Curve= 0 ,0
Exp/Cntr=0.3,0.1

Type RM Length L Ch R = 1 ,10064   ,215.6,209.2,202.6
XS GIS Cut Line= 2
2067443.43605214379714.9227339642066571.40252706379646.527947684
#Sta/Elev= 30
       0  3048.6    10.3 3045.17    30.1 3043.91    79.4 3022.13   161.7 2995.16
   181.5 2993.03   217.7  2978.9   299.9  2970.9   375.6 2969.27   382.9 2967.86
   401.2 2966.51   422.5 2968.23   438.2 2972.24   470.7 2970.45   483.6 2973.01
   497.4 2980.21   517.1 2977.16   533.6 2978.82   536.9 2980.35   544.6 2988.23
   556.6 2997.45   576.4 3003.95   608.7 3026.28  640.59 3037.48   694.8 3055.42
   721.2 3054.57   744.2 3051.56   770.4 3055.92   802.8 3071.68   874.7 3113.32
#Mann= 4 ,-1 , 0
       0      .1       0   382.9    .045       0   422.5      .1       0
  640.59    .055       0
#XS Ineff= 2 , 0
                          443.07         2975.34
Permanent Ineff=
       F       F
Bank Sta=382.9,422.5
XS Rating Curve= 0 ,0
Exp/Cntr=0.3,0.1

Type RM Length L Ch R = 1 ,9855    ,284.4,284.4,282.1
XS GIS Cut Line= 2
     2067446.615      379360.283     2066564.063      379603.117
#Sta/Elev= 30
       0 3034.67    50.4 3020.65    96.1  3000.5   170.5 2992.76   245.4 2980.02
   371.3 2969.32   402.6 2965.25     416 2965.13   421.3 2963.03   435.9 2952.77
     457 2951.08   470.2 2952.66   493.8 2965.05     521 2963.65   534.6 2973.09
   550.9 2981.13   565.2 2994.08   570.7 2997.11   575.4 2996.52   585.7 2991.77
   597.4 2992.79   629.4 3018.52   646.9 3028.11   670.7 3033.67  727.95 3051.98
   776.3 3051.47   799.7 3056.82   826.9 3067.92   850.5 3079.42   915.4 3116.71
#Mann= 4 ,-1 , 0
       0      .1       0   435.9    .045       0   470.2      .1       0
  727.95    .055       0
Bank Sta=435.9,470.2
XS Rating Curve= 0 ,0
Exp/Cntr=0.3,0.1