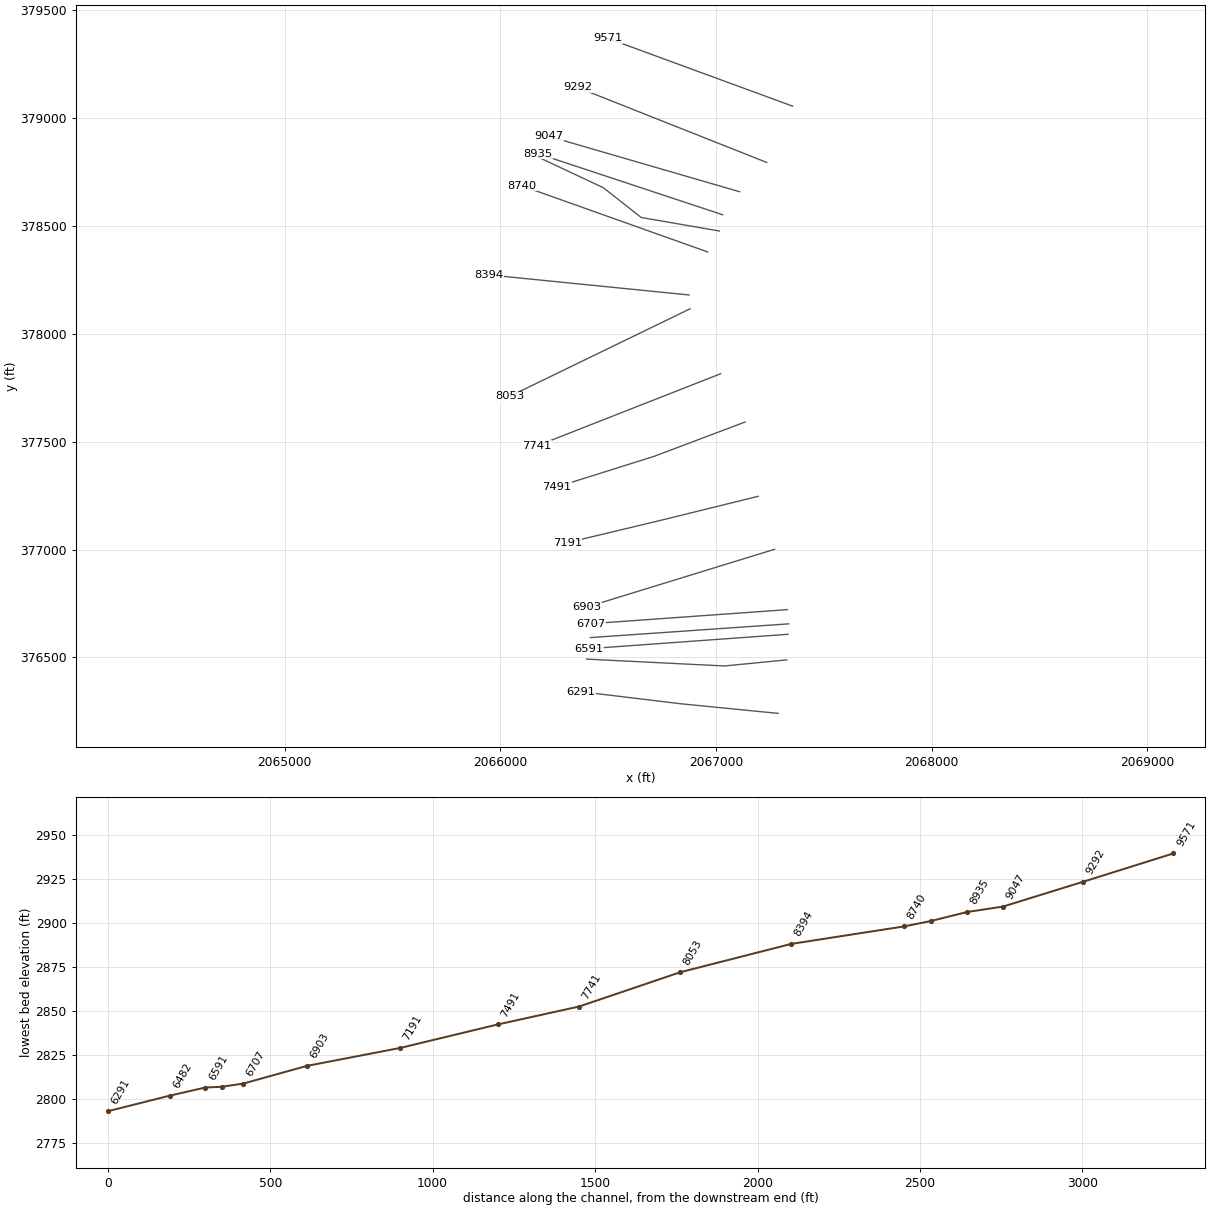
HEC-RAS study BROWNCK.prj: BROWNCK

--- BROWNCK.g01 (geometry) --- (continued)

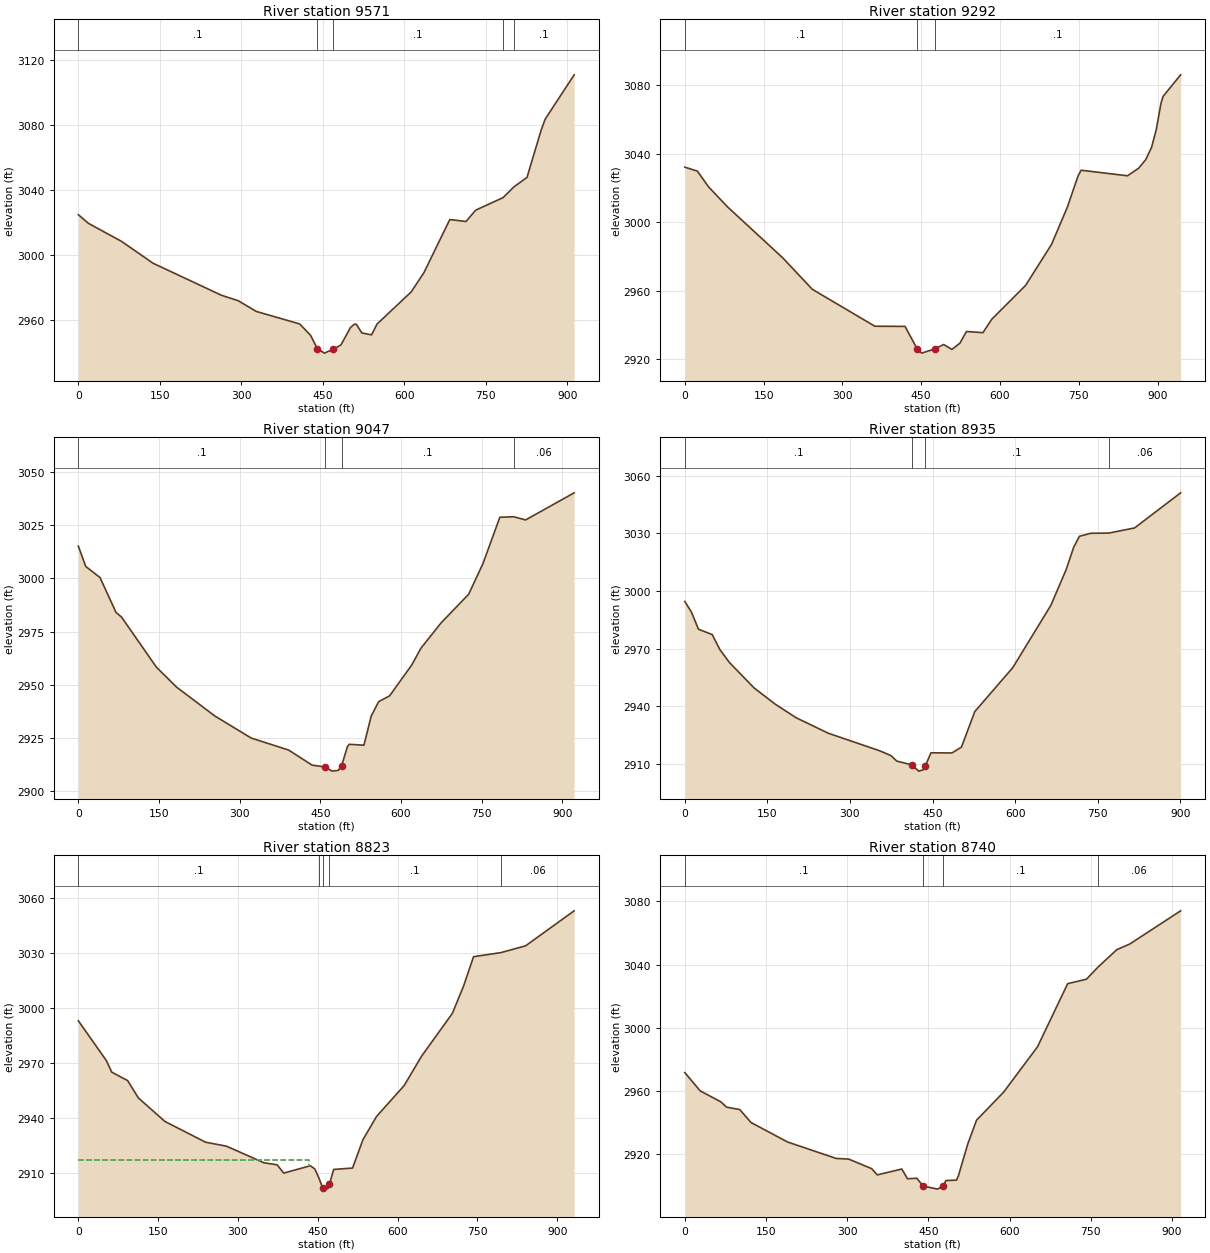
Type RM Length L Ch R = 1 ,9571    ,278.4,278.8,277.6
XS GIS Cut Line= 2
     2067355.482      379055.127     2066498.607      379369.468
#Sta/Elev= 30
       0 3024.87    18.6 3019.54    79.6 3008.43   137.5 2994.99   263.6 2975.25
   294.3 2971.92   327.6 2965.31   407.5 2957.61   427.5 2950.61     440 2942.42
   452.8 2939.65   469.4 2942.05   483.5 2944.72   500.9 2955.36   507.9 2957.44
   511.6 2957.44   521.9 2952.09   539.8 2950.89   549.8 2957.53   612.7 2977.32
   636.2  2989.2   683.8 3021.88   713.6 3020.68   731.4 3027.64  781.97 3035.39
  802.03 3042.05   825.9 3047.81   851.7 3076.65   859.3 3083.65   912.7 3110.96
#Mann= 5 ,-1 , 0
       0      .1       0     440    .045       0   469.4      .1       0
  781.97    .055       0  802.03      .1       0
Bank Sta=440,469.4
XS Rating Curve= 0 ,0
Exp/Cntr=0.3,0.1

Type RM Length L Ch R = 1 ,9292    ,240.9,245,240.9
XS GIS Cut Line= 2
2067235.65031349378794.1402901572066358.17022278379141.802602883
#Sta/Elev= 30
       0 3032.12      24 3029.79    45.2 3020.63    81.2 3008.95   186.4 2979.15
   242.8 2960.75   361.8 2939.19   419.3 2939.09   442.7 2925.69     451 2923.48
   476.2 2926.01   492.8 2928.51   508.4 2925.64   523.6 2929.26   536.2 2936.13
   567.5 2935.43   584.2 2943.24   648.7 2963.03   698.1 2987.02   728.3 3008.81
   748.5 3026.97   754.5 3030.32   842.7 3027.07   863.9 3031.49   877.4 3036.49
   888.6 3043.77   897.6 3054.29   906.3 3069.26   910.3 3073.41   943.8 3086.05
#Mann= 3 ,-1 , 0
       0      .1       0   442.7    .045       0   476.2      .1       0
Bank Sta=442.7,476.2
XS Rating Curve= 0 ,0
Exp/Cntr=0.3,0.1

Type RM Length L Ch R = 1 ,9047    ,111.8,111.7,110.2
XS GIS Cut Line= 2
2067110.00988619378658.3721742182066224.21939105378915.461763836
#Sta/Elev= 30
       0 3015.19    13.8 3005.63    40.3 3000.44    70.1 2984.03    80.3 2981.86
   145.2 2958.31   182.8 2948.91   254.1 2935.33   321.5    2925   391.2 2919.35
   434.8 2912.27   458.7 2911.41   471.9 2909.45   483.4  2909.8   489.6 2911.85
   500.5 2920.94   503.9 2922.05   531.3 2921.64   544.9 2935.39   558.6 2942.07
   579.1 2944.85   620.2 2959.33   637.2 2967.17   674.8 2979.12     726 2992.54
   752.6 3006.93   784.1 3028.74  809.79 3028.99     832 3027.48   922.3 3040.22
#Mann= 4 ,-1 , 0
       0      .1       0   458.7    .045       0   489.6      .1       0
  809.79     .06       0
Bank Sta=458.7,489.6
XS Rating Curve= 0 ,0
Exp/Cntr=0.5,0.3

Type RM Length L Ch R = 1 ,8935    ,113,112.1,108.3
XS GIS Cut Line= 2
2067030.91434649378551.8252006112066175.87265112378834.594895141
#Sta/Elev= 30
       0 2994.52    11.8 2989.16    24.9 2980.06    49.8 2977.32    63.6 2969.56
    80.9 2962.85   125.8 2949.58   163.8 2941.22   201.8 2934.12   260.6 2926.01
   353.9 2916.89   374.6 2914.35     385 2911.52   412.6 2909.54   424.8  2906.3
   433.3 2907.01   436.8 2909.04   447.2 2915.83   485.2 2915.75   502.5 2918.79
   526.7 2937.26   595.8 2960.14   664.9 2992.51   692.5 3010.96   706.3 3022.66
   716.7 3028.41   737.4 3029.99  770.27 3030.09   816.9 3032.75   900.6 3051.02
#Mann= 4 ,-1 , 0
       0      .1       0   412.6    .045       0   436.8      .1       0
  770.27     .06       0
#XS Ineff= 2 , 0
             370  2914.5     447          2914.5
Permanent Ineff=
       F       F
Bank Sta=412.6,436.8
XS Rating Curve= 0 ,0
Exp/Cntr=0.5,0.3

Type RM Length L Ch R = 1 ,8823    ,77.6,82.9,88.7
XS GIS Cut Line= 4
2067015.98772203378476.3626994152066653.36948203378539.104221295
2066477.57114041378677.1868906322066169.40988147378821.745683448
#Sta/Elev= 30
       0 2993.04    52.8 2971.27    62.8    2965    92.7 2960.39   112.7 2950.98
   162.7  2938.1   239.2 2926.77   278.3 2924.61   348.9 2915.54   373.6 2914.44
   386.1 2909.91   436.1 2913.92   444.5 2912.18     452 2907.35     459 2901.96
   461.2 2901.16   469.3  2901.5   471.8 2903.69   479.9 2911.91   515.4 2912.66
   534.8 2928.07   560.5 2940.83   612.4 2957.67   645.1  2973.7     703 2997.08
   724.1 3012.02   742.8    3028  794.62 3030.26   840.7 3033.95   931.9 3053.04
#Mann= 5 ,-1 , 0
       0      .1       0     452    .045       0     459      .1       0
   471.8      .1       0  794.62     .06       0
#XS Ineff= 2 , 0
           433.5 2916.87
Permanent Ineff=
       F       F
Bank Sta=459,471.8
XS Rating Curve= 0 ,0
Exp/Cntr=0.5,0.3

Type RM Length L Ch R = 1 ,8740    ,337.9,345.9,350.4
XS GIS Cut Line= 2
2066961.20954795 378379.468922452066098.01177432378686.418311267
#Sta/Elev= 30
       0 2971.75    28.4  2960.2    66.7 2953.24    77.2  2949.9   101.5 2948.39
   122.4 2940.18   189.8 2927.89   279.7 2917.49   302.8 2917.08   345.3 2911.03
   355.7 2907.09     401  2910.8   411.4 2904.66   428.9 2904.94   440.1 2900.05
   467.3 2898.09   477.1 2900.29   482.6 2903.52     502 2903.79   505.5 2906.47
   522.9  2926.7   539.1 2941.69     589 2959.35   651.7 2988.06   707.4 3027.94
   742.2 3030.77   763.1 3038.29     798 3049.38   822.3 3053.04   916.1 3073.98
#Mann= 4 ,-1 , 0
       0      .1       0   440.1    .045       0   477.1      .1       0
   763.1     .06       0
Bank Sta=440.1,477.1
XS Rating Curve= 0 ,0
Exp/Cntr=0.3,0.1

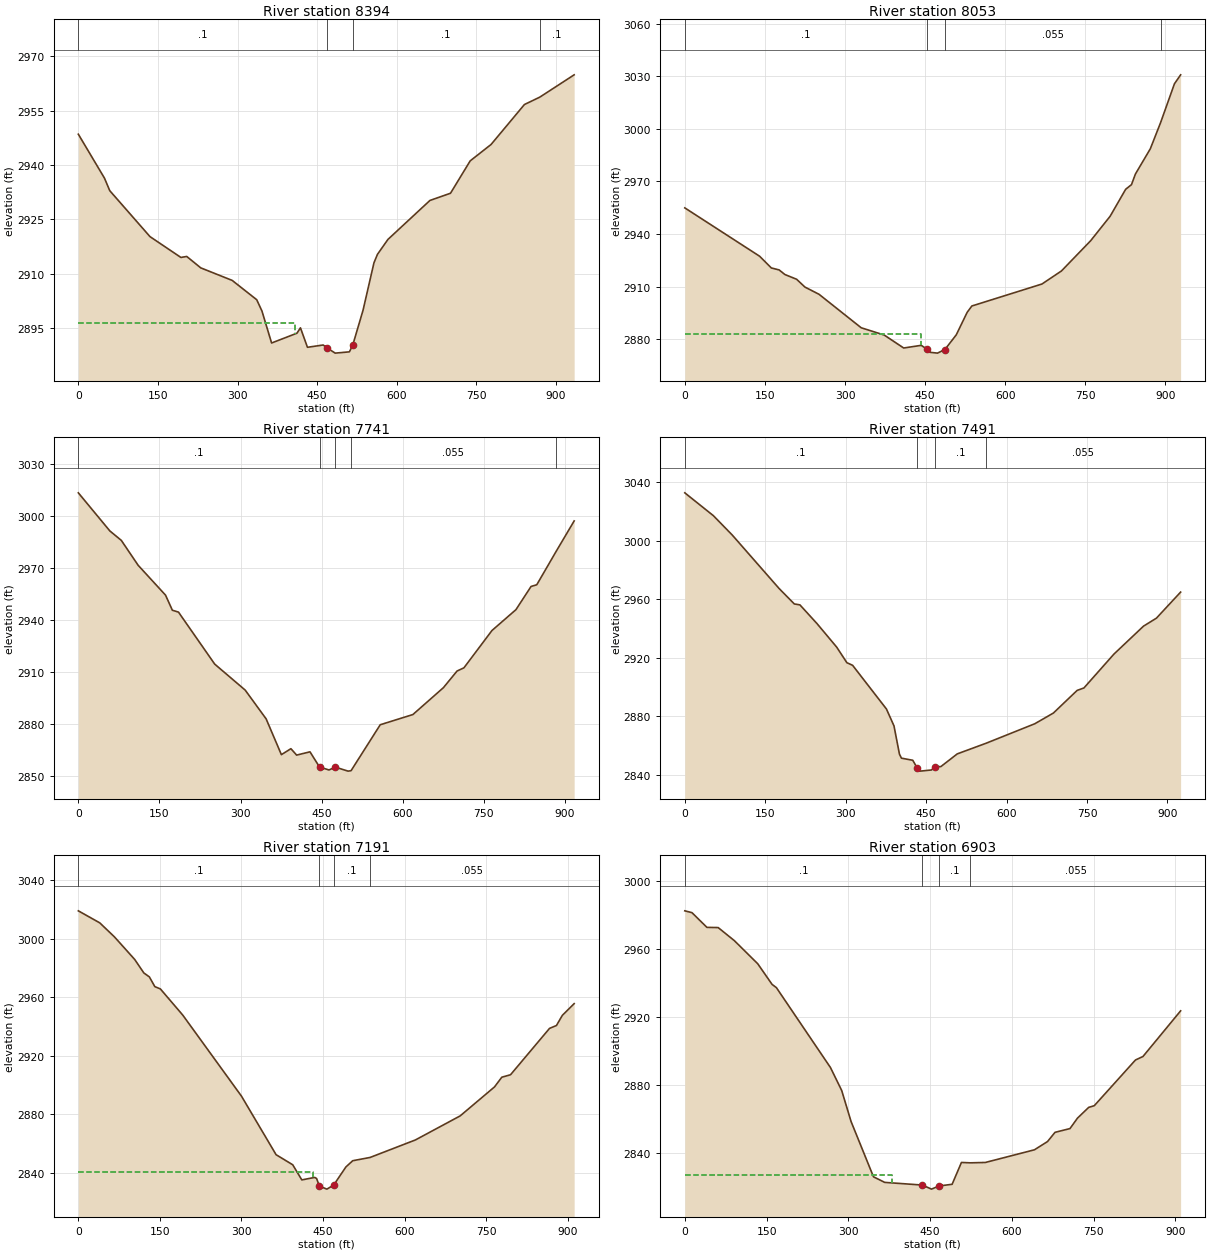
Type RM Length L Ch R = 1 ,8394    ,331.2,341.6,354
XS GIS Cut Line= 2
2066875.26096215378179.9045166822065945.50155166378273.001362726
#Sta/Elev= 30
       0 2948.49    49.3 2936.38    59.2 2932.94   135.1 2920.27   193.3 2914.54
   204.3 2914.81   230.7 2911.67     290 2908.21   336.2 2902.89   346.1 2899.76
   364.2 2890.97     412 2893.67   418.6 2895.15   431.8 2889.79   461.5 2890.42
   469.1 2889.58   484.1 2888.18   510.8 2888.53     517 2890.31   536.5 2899.97
   557.1 2913.05   563.7 2915.39   583.5 2919.51   662.6 2930.24   701.4 2932.23
   738.5 2941.15   777.8 2945.66   840.7 2956.67  869.63  2958.7   934.4 2964.85
#Mann= 4 ,-1 , 0
       0      .1       0   469.1    .045       0     517      .1       0
  869.63      .1       0
#XS Ineff= 2 , 0
          408.09 2896.57
Permanent Ineff=
       F       F
Bank Sta=469.1,517
XS Rating Curve= 0 ,0
Exp/Cntr=0.3,0.1

Type RM Length L Ch R = 1 ,8053    ,310.1,311.3,305.2
XS GIS Cut Line= 2
2066880.09716195378115.8248694062066044.64364745377710.793136618
#Sta/Elev= 30
       0 2954.89   140.1 2927.32     162 2920.64   176.6 2919.52   187.5 2916.88
   209.4 2914.19     225 2909.73   251.4 2905.61   330.3 2886.54   373.5 2882.37
   409.9 2874.99   442.8 2876.51   453.7 2874.31   458.2 2872.58   473.2 2872.07
   487.1 2874.13   508.4 2882.51   528.8 2895.34   537.6 2898.95   668.8 2911.47
   705.3 2918.91     760 2936.15   796.5 2950.11   825.6  2965.5   836.5 2968.14
   843.8 2974.16   871.8 2988.61  891.14 3003.62   916.9 3025.62   928.5 3030.75
#Mann= 4 ,-1 , 0
       0      .1       0   453.7    .045       0   487.1    .055       0
  891.14      .1       0
#XS Ineff= 2 , 0
           442.8  2882.7
Permanent Ineff=
       F       F
Bank Sta=453.7,487.1
XS Rating Curve= 0 ,0
Exp/Cntr=0.3,0.1

Type RM Length L Ch R = 1 ,7741    ,252.3,250.7,249.8
XS GIS Cut Line= 2
2067021.55600593377814.7714321992066167.96674221377479.864596431
#Sta/Elev= 30
       0 3013.35    58.3 2991.33    79.5 2985.88   110.6  2971.5   161.3 2954.23
   173.9 2945.52   185.2 2944.44   252.2  2914.4   308.6 2899.37   347.3 2882.76
   375.5 2862.09   393.1 2865.53   403.7 2861.83   428.4 2863.72     446 2854.95
   463.6 2853.24   475.1 2854.89   498.9 2852.57  504.32 2852.81   558.3 2879.36
   618.7 2885.26   675.1 2900.78   700.4 2910.41   713.1 2912.26   764.9  2933.8
   809.3 2945.87   837.2 2959.25   847.8 2960.25  882.99  2979.2   916.9  2997.1
#Mann= 5 ,-1 , 0
       0      .1       0     446    .045       0   475.1      .1       0
  504.32    .055       0  882.99      .1       0
Bank Sta=446,475.1
XS Rating Curve= 0 ,0
Exp/Cntr=0.3,0.1

Type RM Length L Ch R = 1 ,7491    ,301.9,300,297.9
XS GIS Cut Line= 3
     2067135.315      377591.105     2066712.278        377431.6
     2066261.466      377290.071
#Sta/Elev= 30
       0 3032.66    53.4    3017    88.5 3003.79   175.8 2967.26   204.2 2956.69
   214.7 2956.03   246.2 2943.38   283.2 2927.18   302.3 2916.49   312.9 2914.73
     376 2884.86   390.1 2873.28   400.3 2853.95     404 2851.22   425.1 2849.79
   433.4 2844.52   439.1 2842.36     460 2843.14   466.7 2845.43   477.4 2845.43
   508.1 2854.15  561.83 2861.42   652.7 2874.76   687.3 2882.06   731.6 2897.55
   744.3 2899.24   800.4 2922.44   855.4 2941.49   879.5 2946.97   924.6 2964.77
#Mann= 4 ,-1 , 0
       0      .1       0   433.4    .045       0   466.7      .1       0
  561.83    .055       0
Bank Sta=433.4,466.7
XS Rating Curve= 0 ,0
Exp/Cntr=0.3,0.1

Type RM Length L Ch R = 1 ,7191    ,285.2,287.7,287.1
XS GIS Cut Line= 3
     2067195.743      377246.707     2066751.914      377137.248
     2066309.741      377031.582
#Sta/Elev= 30
       0 3019.01    39.4  3010.8    66.4 3001.23   103.6 2985.84   120.5 2976.59
   130.6 2973.91   140.7 2967.26   150.9 2965.69     192 2947.85     300  2892.5
   363.7  2852.5   394.2 2845.66     411 2835.31   434.7    2837   438.1 2836.29
   443.4 2831.03   457.1 2829.01   469.6 2831.79   492.1 2844.17   504.6  2848.4
  536.58 2850.64   619.9 2862.59   702.2 2879.01   765.3 2898.78   778.8 2905.43
   794.8  2907.1   866.5 2938.75   879.2  2940.7   890.1 2947.66   911.8 2955.64
#Mann= 4 ,-1 , 0
       0      .1       0   443.4    .045       0   469.6      .1       0
  536.58    .055       0
#XS Ineff= 2 , 0
          431.74 2840.41
Permanent Ineff=
       F       F
Bank Sta=443.4,469.6
XS Rating Curve= 0 ,0
Exp/Cntr=0.3,0.1

Type RM Length L Ch R = 1 ,6903    ,198.1,195.6,191.9
XS GIS Cut Line= 2
 2067271.8293453377001.0808167782066402.52243224376733.880778133
#Sta/Elev= 30
       0 2982.65    13.1 2981.58    40.6 2972.91    61.2 2972.79      91 2965.06
   133.8 2951.48   160.1 2939.32     168 2937.42   267.2 2890.35   287.8 2876.83
   304.9 2858.64   346.1 2826.02   366.7 2822.74   435.8 2821.16   452.5 2818.77
   466.2 2820.62   490.3 2821.62   507.4 2834.47  523.83 2834.25   551.3 2834.47
   641.3 2841.93   665.3 2846.79     679 2852.21   706.5 2854.43   720.2 2860.56
   740.8 2866.91   751.1 2867.92   826.6 2894.81   840.4 2896.89   909.4 2923.75
#Mann= 4 ,-1 , 0
       0      .1       0   435.8    .045       0   466.2      .1       0
  523.83    .055       0
#XS Ineff= 2 , 0
          380.24 2827.16
Permanent Ineff=
       F       F
Bank Sta=435.8,466.2
XS Rating Curve= 0 ,0
Exp/Cntr=0.3,0.1

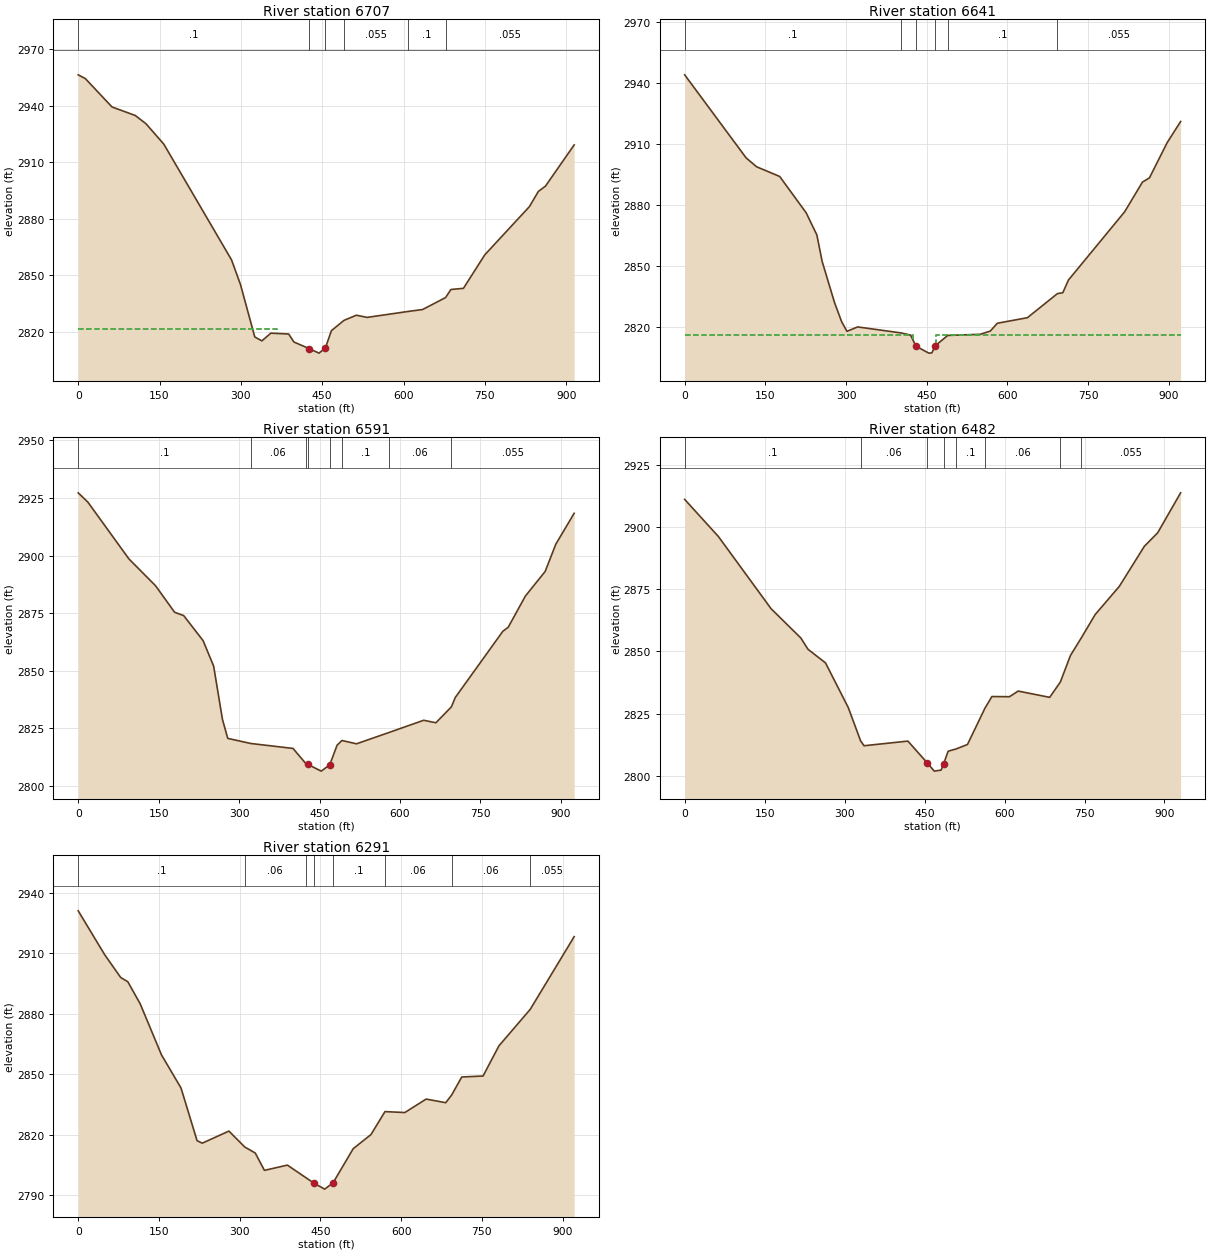
Type RM Length L Ch R = 1 ,6707    ,65.4,66.4,65.9
XS GIS Cut Line= 2
2067331.36999244 376721.423928722066419.12367046376656.376799674
#Sta/Elev= 30
       0  2956.5    13.1 2954.52    62.4 2939.42   105.2 2934.92   124.9 2930.56
   157.8 2919.73   282.8 2858.22   299.3 2845.11   325.6 2817.33   338.7 2815.24
   355.2 2819.33   388.1 2818.89   397.9 2814.62   425.7 2811.16     444 2808.73
   455.7 2811.42     467 2820.67     490  2826.1   513.1 2828.87   532.8  2827.7
   608.4 2830.86   635.2 2831.89   677.5 2838.24   687.4 2842.53   710.4 2843.13
   749.9 2860.96   832.1 2886.52   848.6 2894.58   861.7  2897.4   914.6 2919.29
#Mann= 6 ,-1 , 0
       0      .1       0   425.7    .045       0   455.7      .1       0
     490    .055       0   608.4      .1       0   677.5    .055       0
#XS Ineff= 2 , 0
          366.22 2821.46
Permanent Ineff=
       F       F
Bank Sta=425.7,455.7
XS Rating Curve= 0 ,0
Exp/Cntr=0.5,0.3

Type RM Length L Ch R = 1 ,6641    ,50,50.1,50.5
XS GIS Cut Line= 2
2067337.01038509376655.4963869662066417.41908467376591.839907171
#Sta/Elev= 30
       0 2944.09   114.1 2903.19   133.5 2898.79   176.6 2893.99   225.8 2876.09
   245.7 2865.16   255.5 2852.14   278.4 2831.95   291.7 2822.43   301.6 2817.66
   321.5 2819.83   402.4 2816.86   419.9  2815.8   429.8 2810.36   453.7 2806.91
   459.4 2807.03     466 2810.62     489 2815.63   549.1 2816.19     568 2817.76
   581.1 2821.63     637 2824.37   692.9 2836.26   702.8 2836.66   713.3 2842.93
   817.9 2876.62   850.8 2891.19   863.9 2893.32   896.8 2910.66   921.8 2921.08
#Mann= 6 ,-1 , 0
       0      .1       0   402.4     .06       0   429.8    .045       0
     466     .06       0     489      .1       0   692.9    .055       0
#XS Ineff= 2 , 0
          424.35    2816  466.42            2816
Permanent Ineff=
       F       F
Bank Sta=429.8,466
XS Rating Curve= 0 ,0
Exp/Cntr=0.5,0.3

Type RM Length L Ch R = 1 ,6591    ,112.6,108.6,105.9
XS GIS Cut Line= 2
2067334.01217785376607.1320227572066411.48288605376540.537551587
#Sta/Elev= 30
       0 2927.26      18 2923.23    94.7 2898.55   144.4 2886.91   179.8 2875.42
   196.7 2873.99   232.9 2863.13   252.6 2852.05     269 2828.96   278.9 2820.71
   321.6  2818.5   400.6 2816.35   424.4 2809.81   428.1 2809.44   453.2  2806.5
     469 2809.21   482.8 2817.75   491.8  2819.8     519 2818.35   579.4 2823.25
   644.3 2828.57   667.1 2827.48     696  2834.4   703.2 2838.45     792 2867.21
   801.9 2868.92     834 2882.48   870.9 2893.16   890.7 2904.98   924.9 2918.38
#Mann= 8 ,-1 , 0
       0      .1       0   321.6     .06       0   424.4    .045       0
   428.1    .045       0     469     .06       0   491.8      .1       0
   579.4     .06       0     696    .055       0
Bank Sta=428.1,469
XS Rating Curve= 0 ,0
Exp/Cntr=0.5,0.3

Type RM Length L Ch R = 1 ,6482    ,191.7,191.7,189.7
XS GIS Cut Line= 3
 2067328.6104955376488.5322393552067038.63074677376460.327522153
2066400.49902009376492.057829005
#Sta/Elev= 30
       0    2911    63.3 2896.09     162 2867.14     218 2855.34   231.2 2850.86
   264.2 2845.36     307 2827.38  330.02 2814.06   336.5  2812.1   418.7 2813.97
   455.4 2805.13   468.2 2801.91   481.1 2802.33   485.9 2804.94   494.2  2809.9
  509.55 2810.84   530.5 2812.61  563.08  2827.1   576.3 2831.86   609.2 2831.78
   625.6 2834.05   684.7 2831.53  704.63 2837.65   723.7 2848.35  743.55 2855.24
   770.1 2864.79   815.3 2876.08   862.2 2892.15   887.3 2897.61   930.3 2913.64
#Mann= 8 ,-1 , 0
       0      .1       0  330.02     .06       0   455.4    .045       0
   485.9     .06       0  509.55      .1       0  563.08     .06       0
  704.63     .06       0  743.55    .055       0
Bank Sta=455.4,485.9
XS Rating Curve= 0 ,0
Exp/Cntr=0.3,0.1

Type RM Length L Ch R = 1 ,6291    ,220.7,223.4,224.8
XS GIS Cut Line= 3
     2067288.532      376240.572     2066838.429      376284.903
      2066372.79      376341.174
#Sta/Elev= 30
       0 2931.18    49.2 2909.38    78.9 2898.09    92.1 2895.99   115.1 2885.03
   154.7 2859.67     191 2843.21   220.8 2817.06   230.5 2815.83     280 2821.83
  309.31 2813.94   328.9 2810.93   345.9 2802.33   388.6 2804.93   422.9 2798.71
   438.2 2795.94   457.8 2793.01   473.3 2796.08   510.9  2813.1   543.9 2820.11
  569.86  2831.5   606.7 2831.03   646.4 2837.72   682.7 2835.92  693.69 2839.71
   712.5 2848.68   752.1 2849.17   781.5 2864.12  839.75 2882.28   921.3 2918.34
#Mann= 8 ,-1 , 0
       0      .1       0  309.31     .06       0   422.9      .1       0
   438.2    .045       0   473.3      .1       0  569.86     .06       0
  693.69     .06       0  839.75    .055       0
Bank Sta=438.2,473.3
XS Rating Curve= 0 ,0
Exp/Cntr=0.3,0.1