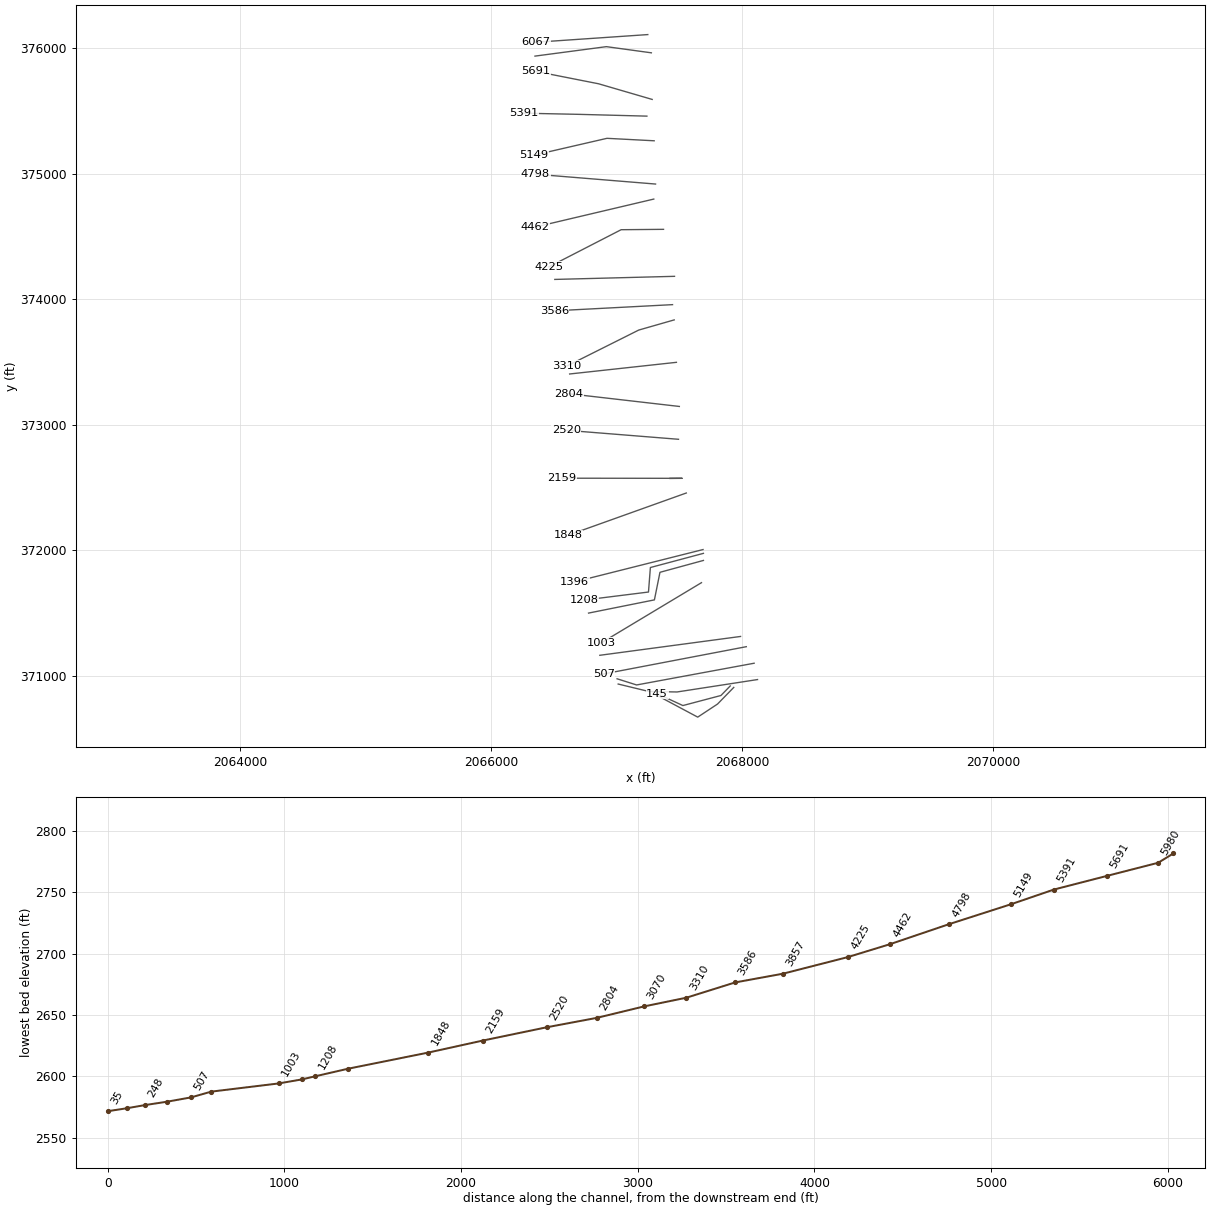
HEC-RAS study BROWNCK.prj: BROWNCK

--- BROWNCK.g01 (geometry) --- (continued)

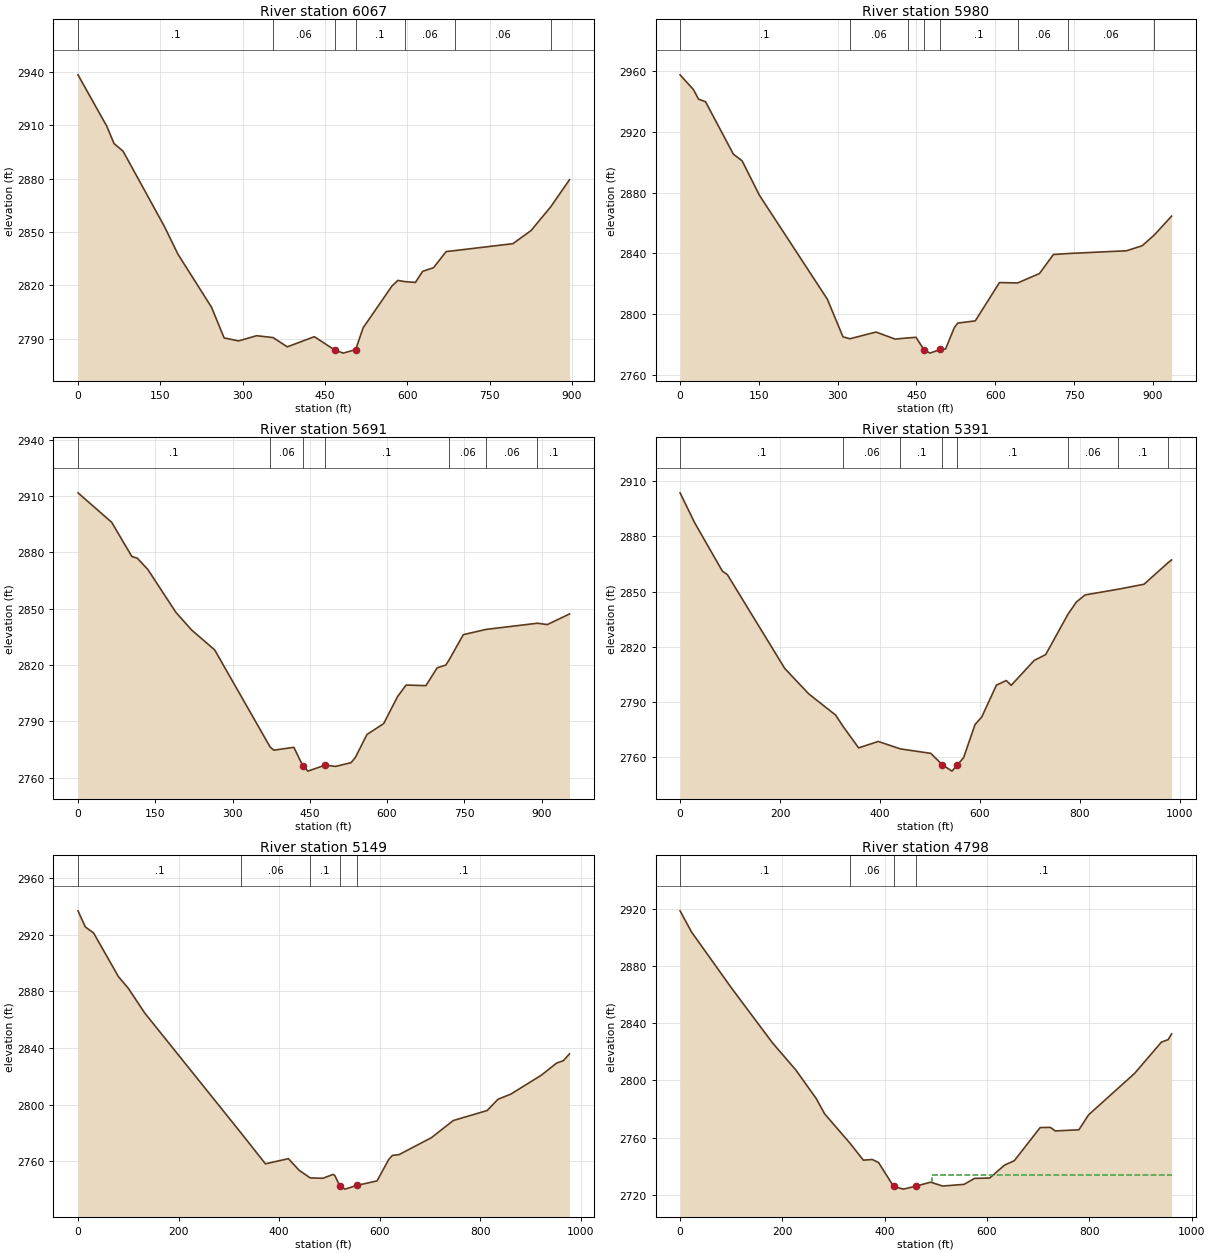
Type RM Length L Ch R = 1 ,6067    ,85.7,86.7,87.5
XS GIS Cut Line= 2
2067246.06568332376109.4899361312066352.57103614376048.426985369
#Sta/Elev= 30
       0 2938.51    52.6 2909.51    65.7 2899.84    82.2 2895.49   157.8 2852.96
   182.1 2837.57   243.3 2807.69   266.3 2790.41   292.6 2788.73   325.5 2791.67
   355.5  2790.6   381.4  2785.4   430.7 2791.11   467.6 2783.65   483.4 2781.86
     506 2783.88   519.5 2796.08   572.1 2819.64   582.9  2822.8   595.2 2822.13
   595.2 2822.12   614.9 2821.66     628  2827.9   647.8 2829.94   670.8 2839.03
   686.9 2839.58   792.5 2843.47   825.4 2850.82   861.5 2864.27   895.6 2879.47
#Mann= 7 ,-1 , 0
       0      .1       0   355.5     .06       0   467.6    .045       0
     506      .1       0   595.2     .06       0   686.9     .06       0
   861.5      .1       0
Bank Sta=467.6,506
XS Rating Curve= 0 ,0
Exp/Cntr=0.3,0.1

Type RM Length L Ch R = 1 ,5980    ,292.7,289.9,276.8
XS GIS Cut Line= 3
2067274.45989585375964.1811402822066915.90742843376013.363115902
2066347.14167811375938.003637129
#Sta/Elev= 30
       0 2957.61    25.3 2947.96    35.2 2941.58    48.5 2939.85   101.5 2905.29
     118    2901   151.1 2878.21   280.3 2809.77   310.1 2784.94  323.25 2783.68
     373  2788.1   409.4 2783.45  434.52 2784.26   449.1 2784.62     464 2776.56
   475.6 2774.21   495.5 2776.66   505.4 2776.96   521.9 2790.93   528.5 2793.98
   561.9 2795.47     608 2820.72  642.55 2820.46   684.1 2826.66   710.6 2839.19
  739.12 2839.86   849.6 2841.66   879.4 2844.94   902.5    2852   935.6  2864.5
#Mann= 8 ,-1 , 0
       0      .1       0  323.25     .06       0  434.52      .1       0
     464    .045       0   495.5      .1       0  642.55     .06       0
  739.12     .06       0   902.5      .1       0
Bank Sta=464,495.5
XS Rating Curve= 0 ,0
Exp/Cntr=0.3,0.1

Type RM Length L Ch R = 1 ,5691    ,289.5,300,288.7
XS GIS Cut Line= 3
     2067280.958      375592.827     2066853.294      375717.625
     2066354.186      375816.113
#Sta/Elev= 30
       0 2911.75    65.4 2896.06   104.6 2877.81   114.9 2876.99   135.4    2871
   190.1 2848.07   220.8 2838.62   265.3 2828.11  373.02 2776.34   380.2 2774.67
   419.1 2776.19   436.8 2766.09   446.4  2763.5   479.7  2766.7   499.9 2766.01
   530.2 2768.01   538.6 2770.86   560.9 2782.99   593.5 2788.84   620.3 2803.17
     637 2809.37   675.4 2809.03   697.2 2818.52   713.9 2819.98  719.89 2822.47
     748  2836.2  792.45 2839.01  891.84 2842.28   911.2 2841.57   954.2 2847.22
#Mann= 7 ,-1 , 0
       0      .1       0  373.02     .06       0   436.8    .045       0
   479.7      .1       0  719.89     .06       0  792.45     .06       0
  891.84      .1       0
Bank Sta=436.8,479.7
XS Rating Curve= 0 ,0
Exp/Cntr=0.3,0.1

Type RM Length L Ch R = 1 ,5391    ,235,242.1,242.1
XS GIS Cut Line= 3
     2067238.955      375459.693     2066695.278      375473.962
     2066256.062      375483.091
#Sta/Elev= 30
       0 2903.66    28.9 2887.53    84.7 2861.07    94.6  2859.2   209.4 2808.18
   257.4 2794.36   311.2 2782.83  326.29  2776.6   357.1 2765.01   396.5  2768.5
  440.62 2764.46   501.5 2762.03   524.5 2755.85   543.9 2752.37     554 2755.49
   567.2 2759.74     590 2777.69   603.5 2781.83   632.8 2799.12   652.5 2801.63
   662.3 2798.99   708.3 2812.54   731.3 2815.71  775.93 2837.67   792.8 2844.31
     810 2848.14  876.25 2851.25   928.1 2853.97  976.56 2865.79   983.2 2867.19
#Mann= 8 ,-1 , 0
       0      .1       0  326.29     .06       0  440.62      .1       0
   524.5    .045       0     554      .1       0  775.93     .06       0
  876.25      .1       0  976.56     .06       0
Bank Sta=524.5,554
XS Rating Curve= 0 ,0
Exp/Cntr=0.3,0.1

Type RM Length L Ch R = 1 ,5149    ,356.4,351,341.2
XS GIS Cut Line= 3
2067296.85014889 375263.306380662066920.78725287375282.892989828
2066335.14763875375147.745386571
#Sta/Elev= 30
       0 2936.74    14.7 2925.34    31.1 2921.09    80.4 2890.33    99.9 2882.19
   132.9 2864.58  324.45 2779.97   372.8 2758.26   418.4 2761.89     440 2753.68
  461.77 2748.35   486.8 2748.05   507.3 2750.77   510.7 2750.05   520.8 2742.67
   530.9 2740.41   555.2 2743.08   594.9 2746.23   618.1 2761.37   625.2 2764.15
   638.7 2764.77   702.9  2776.7   746.4  2788.8   813.7 2795.85   835.3 2803.79
   860.9 2807.45   921.5 2820.76   951.8 2829.29   965.3 2831.01   977.6 2835.87
#Mann= 5 ,-1 , 0
       0      .1       0  324.45     .06       0  461.77      .1       0
   520.8    .045       0   555.2      .1       0
Bank Sta=520.8,555.2
XS Rating Curve= 0 ,0
Exp/Cntr=0.3,0.1

Type RM Length L Ch R = 1 ,4798    ,326.5,335.7,334.5
XS GIS Cut Line= 2
2067307.92474788 374918.508620722066350.35718858 374996.85505739
#Sta/Elev= 30
       0 2918.47    22.5 2903.63   101.5 2864.11   180.5 2826.35   226.3 2807.34
   266.1 2787.41   282.6 2776.71  332.18 2756.18   358.3 2744.38   375.7 2744.84
   387.9 2742.75   417.5 2726.01   436.5 2724.15   460.9  2726.2   489.9 2729.01
     513 2726.31   555.2 2727.48   575.5 2731.64   605.2  2731.9   634.3 2740.91
   653.3    2744   703.9 2767.14   723.7 2767.26   733.5 2764.78   779.6 2765.59
   798.6 2776.06   888.3 2804.89   940.9 2826.81   954.1 2828.54   960.8 2832.56
#Mann= 4 ,-1 , 0
       0      .1       0  332.18     .06       0   417.5    .045       0
   460.9      .1       0
#XS Ineff= 2 , 0
                          492.11         2734.06
Permanent Ineff=
       F       F
Bank Sta=417.5,460.9
XS Rating Curve= 0 ,0
Exp/Cntr=0.3,0.1

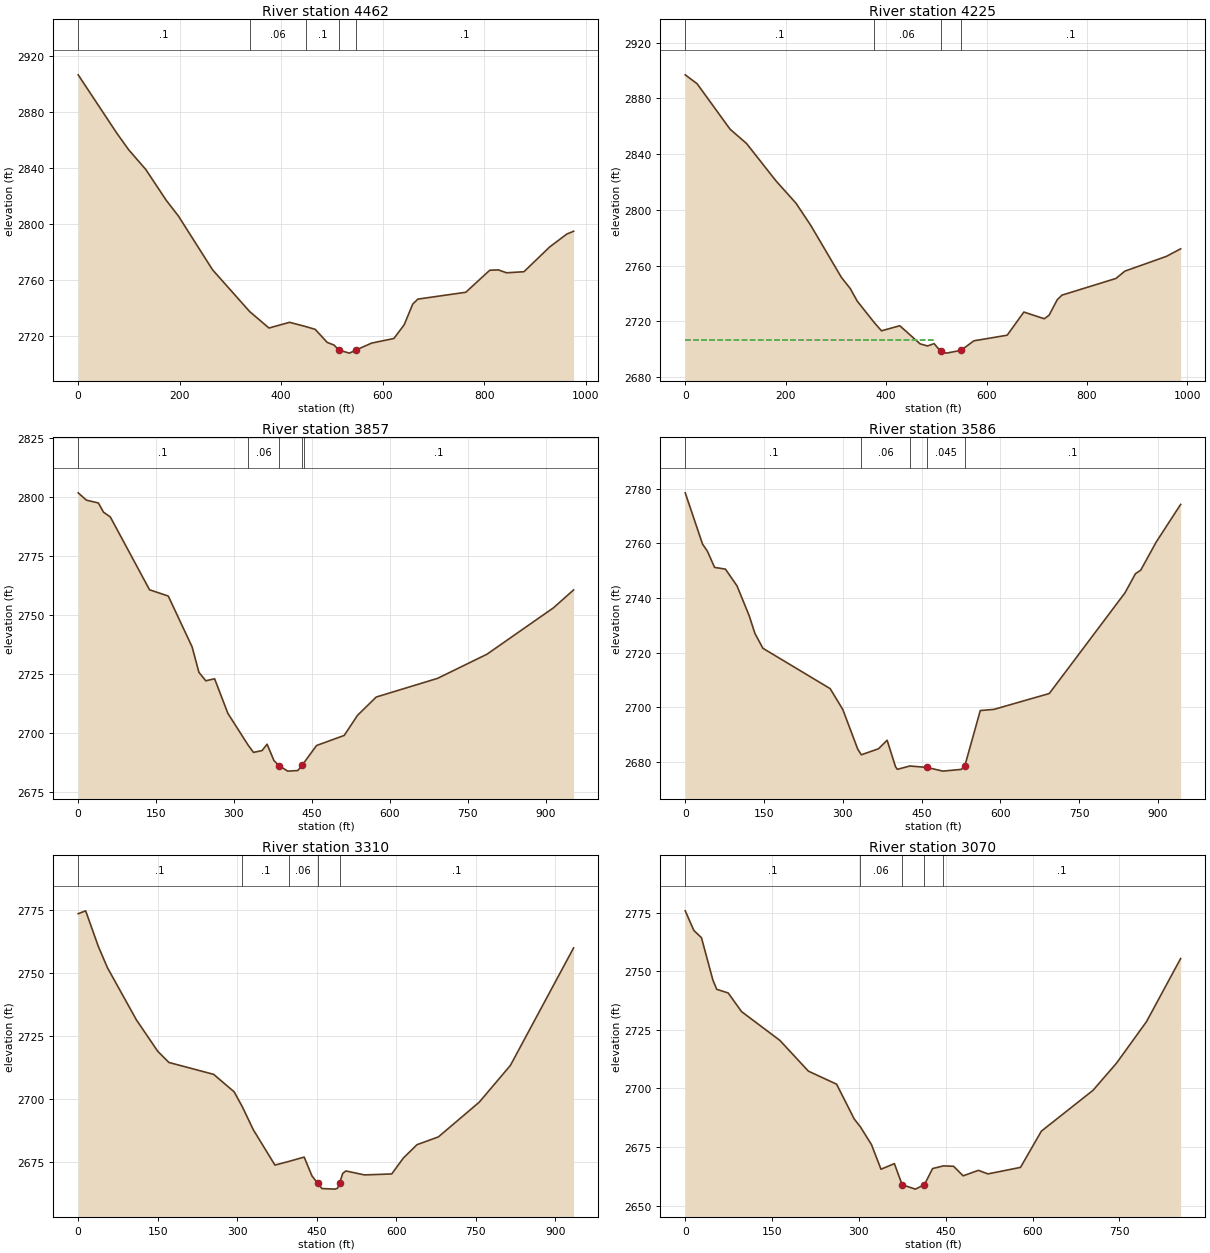
Type RM Length L Ch R = 1 ,4462    ,231.3,237.3,240.1
XS GIS Cut Line= 2
2067293.77886349374798.8126758062066343.82831885374574.654815332
#Sta/Elev= 30
       0  2906.7    75.9 2865.09    99.5 2853.12   133.2 2839.03   173.7 2816.89
   197.3 2805.86   264.7 2767.35  337.88 2737.45   375.9  2725.7   416.4 2729.77
   449.5 2726.63     467 2724.73   490.6 2715.42     504 2713.53   513.9 2709.88
   534.4 2707.75   547.9 2710.06   578.2 2714.93     622 2718.21   642.3 2728.05
   659.1 2742.79   669.2 2746.36   763.6 2751.25   810.8    2767   827.7 2767.26
   843.9 2765.18   878.2 2765.94   928.8 2783.62   962.5 2792.83     976 2794.88
#Mann= 5 ,-1 , 0
       0      .1       0  337.88     .06       0   449.5      .1       0
   513.9    .045       0   547.9      .1       0
Bank Sta=513.9,547.9
XS Rating Curve= 0 ,0
Exp/Cntr=0.3,0.1

Type RM Length L Ch R = 1 ,4225    ,375.5,367.8,357.4
XS GIS Cut Line= 3
2067371.46449037374557.6642200142067033.59548222374554.726228639
2066456.76984224374257.989099749
#Sta/Elev= 30
       0 2896.87    23.6 2890.48    89.3 2857.86   122.1 2847.61   180.8 2820.77
   220.5 2804.83     250 2788.87   310.9 2751.64   328.8  2743.5   342.4 2734.64
  375.68 2719.51   390.8 2713.28   427.3 2716.91   467.8 2703.89   482.6 2702.41
   495.5 2704.12   508.4  2698.7   519.9 2697.27     549 2699.22   574.8  2706.1
   641.2 2710.13   674.4 2726.73     715 2721.92   724.6 2724.47   740.9 2735.61
   750.2 2738.85   857.8 2750.84   875.6 2756.09   958.2 2766.66   986.6 2772.09
#Mann= 4 ,-1 , 0
       0      .1       0  375.68     .06       0   508.4    .045       0
     549      .1       0
#XS Ineff= 2 , 0
          493.26 2706.59
Permanent Ineff=
       F       F
Bank Sta=508.4,549
XS Rating Curve= 0 ,0
Exp/Cntr=0.3,0.1

Type RM Length L Ch R = 1 ,3857    ,263.7,270.3,278.3
XS GIS Cut Line= 2
2067458.90477749374183.2353934482066505.23277711374158.556265897
#Sta/Elev= 30
       0 2801.73    15.9 2798.62    38.9 2797.43    48.8 2793.52    61.9 2791.49
   137.4 2760.61   173.5 2757.95   219.4 2736.39   232.5 2725.61   245.7 2722.02
   262.7 2722.87   288.3 2708.19  327.22 2694.75   337.6 2691.65     354  2692.4
   363.8 2695.12     377 2688.17   386.8 2686.03   403.5  2683.7   422.9 2683.95
   431.7 2686.16  434.54 2687.19     459 2694.56   512.3 2698.84   537.8 2707.34
   573.9 2715.12     692 2723.04   787.2 2733.28   915.2 2752.95     954 2760.55
#Mann= 5 ,-1 , 0
       0      .1       0  327.22     .06       0   386.8    .045       0
   431.7     .06       0  434.54      .1       0
Bank Sta=386.8,431.7
XS Rating Curve= 0 ,0
Exp/Cntr=0.3,0.1

Type RM Length L Ch R = 1 ,3586    ,261.7,276,285
XS GIS Cut Line= 2
2067443.03962406373957.5976558372066500.82579005373908.239400734
#Sta/Elev= 30
       0 2778.55    32.9 2759.78    42.2 2757.16    55.9 2751.23    76.5  2750.6
    98.6 2744.46   121.6 2733.62   132.7 2727.04   147.9  2721.6     276 2706.81
     300 2699.19   328.6 2684.62  335.38 2682.58     368 2684.78   384.5 2687.91
   400.5 2678.19     404 2677.25  427.86 2678.47   460.5 2677.94   490.7 2676.59
   525.7 2677.23   532.3 2678.41   561.9 2698.78   588.1 2699.22   693.3 2705.02
   837.4 2741.89   857.5 2748.94   867.4 2750.19     897 2760.54   943.5 2774.31
#Mann= 5 ,-1 , 0
       0      .1       0  335.38     .06       0  427.86      .1       0
   460.5    .045       0   532.3      .1       0
Bank Sta=460.5,532.3
XS Rating Curve= 0 ,0
Exp/Cntr=0.3,0.1

Type RM Length L Ch R = 1 ,3310    ,246.4,240.2,233.4
XS GIS Cut Line= 3
2067456.56257906373836.0749110842067173.63400963373754.986349129
2066601.60708889373468.532190052
#Sta/Elev= 30
       0 2773.66    14.1 2774.81      38 2760.66    55.1 2752.22   109.7 2731.47
   150.1 2718.93   171.1  2714.5   255.4 2709.78     294 2702.85  309.46 2696.91
   330.1 2687.79     371 2673.69   397.1 2675.14   426.1 2676.88   440.7 2669.44
   451.8 2666.37   459.7 2664.36   484.1 2664.13     489 2664.49   493.1 2666.61
   498.8 2670.38   504.9 2671.36   539.8 2669.78   591.2 2670.17   613.2 2676.51
   638.9 2681.81   679.2  2684.9   756.3 2698.73     815 2713.35   934.1 2760.06
#Mann= 5 ,-1 , 0
       0      .1       0  309.46      .1       0   397.1     .06       0
   451.8    .045       0   493.1      .1       0
Bank Sta=451.8,493.1
XS Rating Curve= 0 ,0
Exp/Cntr=0.3,0.1

Type RM Length L Ch R = 1 ,3070    ,269.1,265.8,261.2
XS GIS Cut Line= 2
2067474.08603428 373497.962005972066623.27310747373405.085741055
#Sta/Elev= 30
       0 2775.92    14.8 2767.57      28 2764.44    47.8 2746.31    54.4 2742.38
    74.2 2740.82    97.3 2732.85   163.4 2720.58   212.8 2707.41   261.5 2701.84
     292 2686.95  302.54 2683.63   321.7 2676.05   338.2  2665.5   361.3 2667.91
   374.7 2658.88   397.6    2657   413.2 2658.91   427.3 2665.79     446 2666.93
   463.6 2666.76   480.1 2662.69   506.5 2665.02     523 2663.51   579.2 2666.29
   615.3 2681.78   704.6 2699.24     745  2710.8   796.9 2728.57   855.9 2755.54
#Mann= 5 ,-1 , 0
       0      .1       0  302.54     .06       0   374.7    .045       0
   413.2     .06       0     446      .1       0
Bank Sta=374.7,413.2
XS Rating Curve= 0 ,0
Exp/Cntr=0.3,0.1

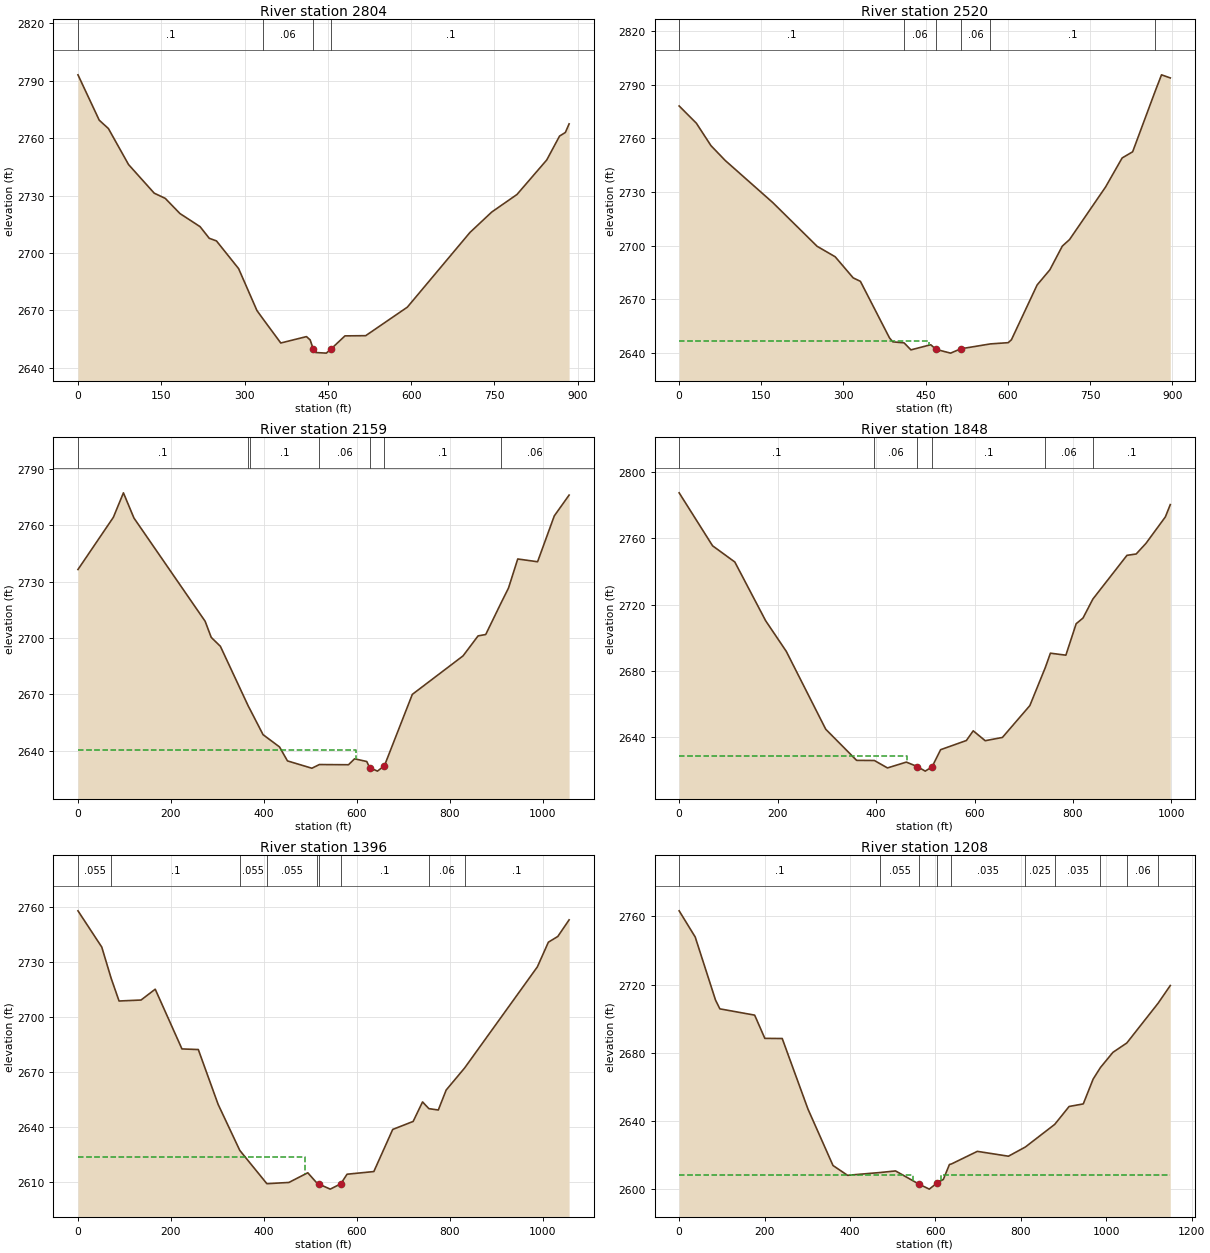
Type RM Length L Ch R = 1 ,2804    ,281.4,284.2,284.1
XS GIS Cut Line= 2
2067497.39368354373146.3590030782066618.79773088373247.527791646
#Sta/Elev= 30
       0 2793.05    38.3 2769.35    54.8    2765    91.1 2746.18   137.3 2731.25
   157.2 2728.52   183.6 2720.62   219.9 2713.75   236.4 2707.69   249.4 2706.31
   289.3 2691.83   322.3 2669.94  332.71 2665.77   365.2    2653   411.5 2656.34
   418.1 2654.61   423.6 2649.93     428 2648.02   447.2 2647.71   456.5 2650.09
   480.8 2656.72   518.1 2656.82   593.1 2671.71   705.9 2710.74     745 2721.37
   790.5 2730.55   844.1 2748.58   867.2 2761.06   877.7 2762.96   884.4 2767.43
#Mann= 4 ,-1 , 0
       0      .1       0  332.71     .06       0   423.6    .045       0
   456.5      .1       0
Bank Sta=423.6,456.5
XS Rating Curve= 0 ,0
Exp/Cntr=0.3,0.1

Type RM Length L Ch R = 1 ,2520    ,357.6,360.8,358.5
XS GIS Cut Line= 2
2067490.67108158372884.6838122472066596.92131008 372956.36807227
#Sta/Elev= 30
       0 2778.16    31.4 2768.54    58.1 2755.98    84.1  2747.7   170.9 2724.17
   251.9 2699.72   284.8 2693.88   317.7 2682.08   330.9 2680.14   384.1 2648.46
   390.2 2646.31  410.66 2645.75   423.1 2641.83   459.3 2644.71   468.8 2642.13
   495.5 2640.01   514.4 2642.44  568.13 2645.16   600.8 2645.86   606.6 2647.49
   653.5 2678.11   676.7 2686.56   699.5 2699.83   712.7 2703.49   778.5 2732.89
   808.7  2749.1   827.9 2752.55     868 2785.57   880.6 2795.57   896.6 2793.84
#Mann= 6 ,-1 , 0
       0      .1       0  410.66     .06       0   468.8    .045       0
   514.4     .06       0  568.13      .1       0     868     .06       0
#XS Ineff= 2 , 0
          456.94 2646.81
Permanent Ineff=
       F       F
Bank Sta=468.8,514.4
XS Rating Curve= 0 ,0
Exp/Cntr=0.3,0.1

Type RM Length L Ch R = 1 ,2159    ,308.6,311.4,318.9
XS GIS Cut Line= 3
2067422.50858469372572.5982677512067520.30371428372573.682610655
2066561.51940046372574.645804456
#Sta/Elev= 30
       0 2736.52    76.2 2764.33    97.8 2777.34   120.4 2763.93   273.6 2708.96
   286.7 2700.39   306.4 2695.64  366.74 2663.65  369.71 2662.28   398.2 2648.61
   433.6 2642.08   450.7 2634.64   503.2 2630.74  519.26  2632.7     582  2632.6
   595.1 2635.76   621.3 2634.32   627.4 2631.11   644.3  2629.2   659.3 2632.08
   719.3 2670.05   828.4 2690.54   860.8 2701.19   877.2 2701.92  910.25 2718.74
   926.2 2726.64   946.1 2742.13   988.8 2740.65  1024.7 2765.05  1056.6 2776.14
#Mann= 7 ,-1 , 0
       0      .1       0  366.74    .055       0  369.71      .1       0
  519.26     .06       0   627.4    .045       0   659.3      .1       0
  910.25     .06       0
#XS Ineff= 2 , 0
          597.22 2640.51
Permanent Ineff=
       F       F
Bank Sta=627.4,659.3
XS Rating Curve= 0 ,0
Exp/Cntr=0.3,0.1

Type RM Length L Ch R = 1 ,1848    ,448.5,451.8,447.9
XS GIS Cut Line= 2
2067552.73191909372456.7076902782066613.32207908372120.706917075
#Sta/Elev= 30
       0 2787.51    67.9  2755.5   113.1  2745.7   175.7 2710.21   217.6 2691.71
   297.8 2644.62   360.5 2625.81  396.56 2625.74   423.2 2621.24   461.5 2624.76
   483.7 2622.07   499.9 2619.31   513.8 2621.92   531.2 2632.27   583.5 2637.82
   597.4 2643.67   621.8 2637.69   656.7 2639.67   712.4 2658.91  743.85 2681.94
   754.2 2690.59   785.6 2689.39   806.5 2708.39   820.4 2711.83  840.42 2723.29
   909.7 2749.73   928.4 2750.54   948.2 2756.93   987.7 2772.95   997.7 2780.39
#Mann= 6 ,-1 , 0
       0      .1       0  396.56     .06       0   483.7    .045       0
   513.8      .1       0  743.85     .06       0  840.42      .1       0
#XS Ineff= 2 , 0
          462.96 2628.33
Permanent Ineff=
       F       F
Bank Sta=483.7,513.8
XS Rating Curve= 0 ,0
Exp/Cntr=0.3,0.1

Type RM Length L Ch R = 1 ,1396    ,150.4,188.4,211.8
XS GIS Cut Line= 2
2067686.15418734372006.1054361762066661.56682043371748.115811413
#Sta/Elev= 30
       0 2757.97    51.2  2738.2    71.5 2721.09    88.4 2708.79   135.7 2709.33
   166.2 2715.23   223.7 2682.67   258.9 2682.32   301.5 2652.45   348.1 2627.34
   406.4 2609.17   453.8 2609.85   494.4 2615.13   514.7 2609.34   518.1 2608.99
   542.7 2606.21   565.4 2609.12   578.9 2614.34   636.5 2615.79   677.1 2638.75
   721.1 2643.13   741.3 2653.77   754.9 2650.11   775.2 2649.35   792.1 2660.23
   831.9  2672.3   988.3  2727.4    1012 2740.87  1032.3 2743.99  1056.6 2753.04
#Mann= 9 ,-1 , 0
       0    .055       0    71.5      .1       0   348.1    .055       0
   406.4    .055       0   514.7      .1       0   518.1    .045       0
   565.4      .1       0   754.9     .06       0   831.9      .1       0
#XS Ineff= 2 , 0
          489.34 2623.47
Permanent Ineff=
       F       F
Bank Sta=518.1,565.4
XS Rating Curve= 0 ,0
Exp/Cntr=0.5,0.3

Type RM Length L Ch R = 1 ,1208    ,82.1,74.4,70.3
XS GIS Cut Line= 4
2067689.26459768 371975.797997222067266.70015319371862.910744902
 2067251.4451191371667.6463084592066738.87597344371603.575165252
#Sta/Elev= 30
       0 2763.31    37.6 2747.94    85.1 2710.97    95.3 2705.77   176.8 2702.08
   200.6 2688.44   241.3 2688.36   301.5 2646.99   360.2 2613.81   394.2 2608.06
   470.4  2609.7   506.6 2610.63   561.4  2602.9   585.6 2599.95   603.2 2603.42
   618.5 2605.65   632.8 2614.43   637.4 2614.71   698.1 2622.12   770.9 2619.27
   810.5 2624.67   879.3 2637.97     913 2648.47   946.1 2649.97   969.2 2664.54
   986.3 2671.33  1015.5 2680.24    1048 2685.73  1121.5 2709.14  1149.8 2719.46
#Mann= 10 ,-1 , 0
       0      .1       0   470.4    .055       0   561.4    .045       0
   603.2    .055       0   637.4    .035       0   810.5    .025       0
   879.3    .035       0   986.3    .055       0    1048     .06       0
  1121.5      .1       0
#XS Ineff= 2 , 0
          546.42    2608  611.96            2608
Permanent Ineff=
       F       F
Bank Sta=561.4,603.2
XS Rating Curve= 0 ,0
Exp/Cntr=0.5,0.3

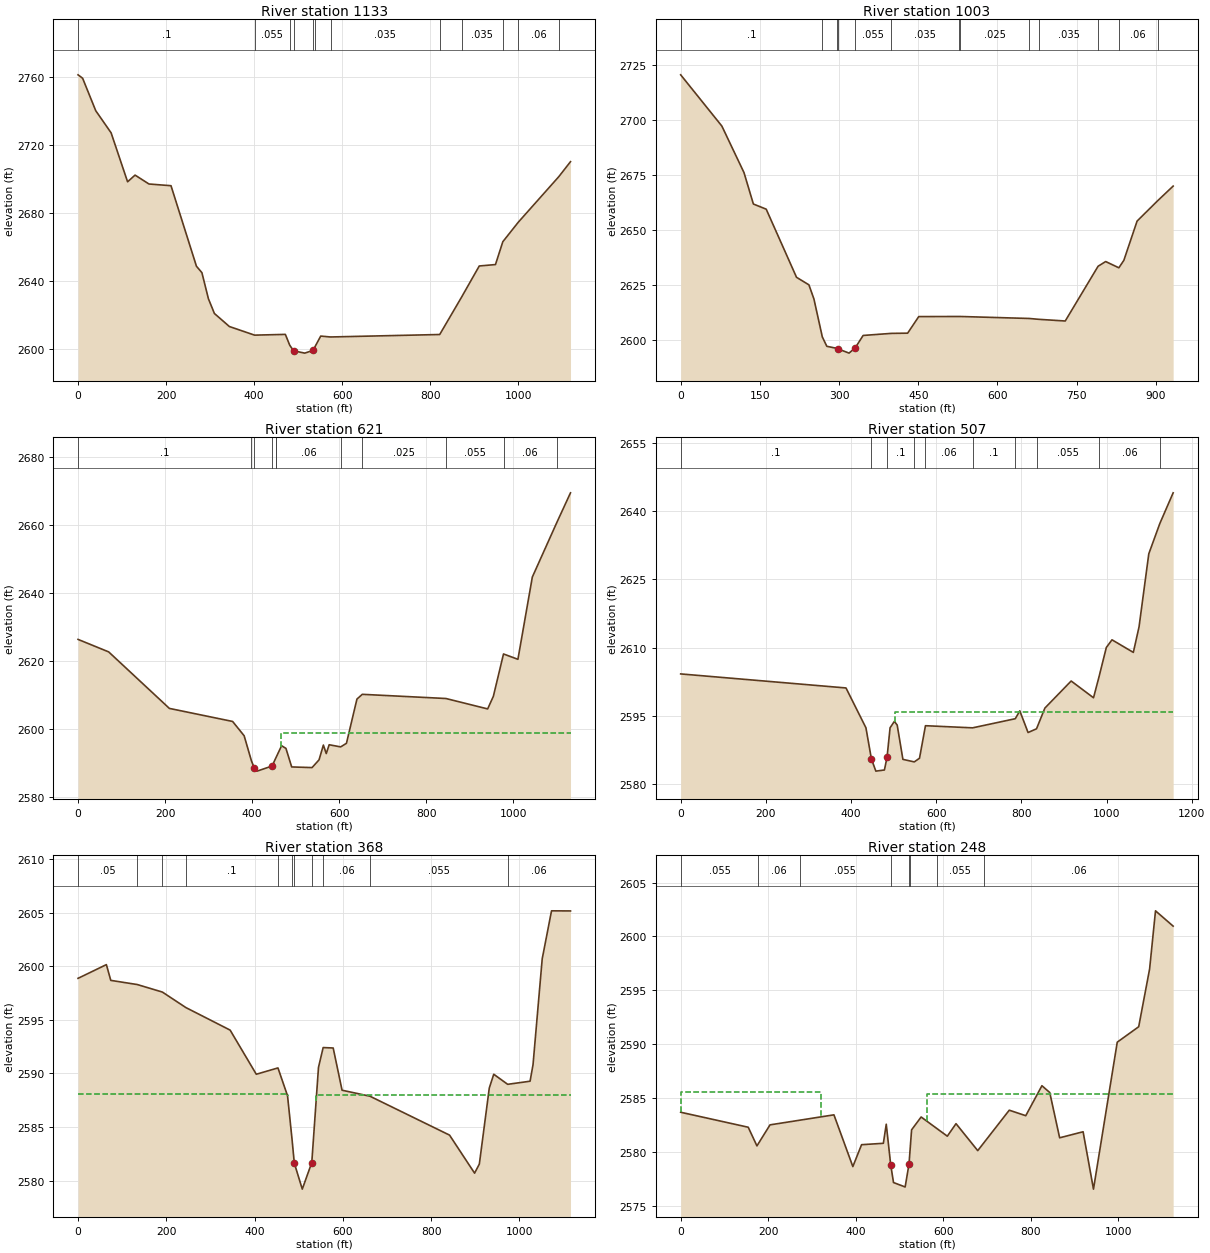
Type RM Length L Ch R = 1 ,1133    ,148.6,130.1,116.3
XS GIS Cut Line= 4
2067689.26459768371919.3543710612067342.97532368371824.773159659
 2067298.7357248371605.1006686612066773.96255186371499.840933392
#Sta/Elev= 30
       0 2761.16    10.4 2759.16    40.2 2740.05    75.1 2727.04   112.5 2698.23
   129.5 2702.17   161.1 2696.94   211.1 2695.93   268.9 2648.56   281.3 2644.78
   296.1 2629.41   309.7 2620.76   343.7  2613.1   400.9 2608.03   470.8 2608.47
   480.8 2602.05   489.7  2598.8   514.8 2597.45   534.3 2599.11   538.7 2601.52
   551.1 2607.48   573.3 2606.95   821.3  2608.4     871 2630.41   911.1 2648.71
   947.9 2649.55   964.6 2662.98   999.9 2674.51  1091.7 2701.24  1118.3 2710.07
#Mann= 12 ,-1 , 0
       0      .1       0   400.9    .055       0   480.8    .045       0
   489.7    .045       0   534.3    .045       0   538.7    .055       0
   573.3    .035       0   821.3    .025       0     871    .035       0
   964.6    .055       0   999.9     .06       0  1091.7      .1       0
Bank Sta=489.7,534.3
XS Rating Curve= 0 ,0
Exp/Cntr=0.5,0.3

Type RM Length L Ch R = 1 ,1003    ,385.1,382,372.3
XS GIS Cut Line= 2
2067673.72413222371742.2027338782066874.02814677371261.917809643
#Sta/Elev= 30
       0 2720.51      78 2697.25   119.9 2676.14   137.7 2661.87     162 2659.53
   219.4 2628.61   242.9 2625.18   252.4 2618.75  268.28 2601.54   276.8 2597.29
   296.8  2596.3   297.2 2596.21   318.9 2594.19   330.7 2596.64   345.6 2602.21
  398.87 2603.15   429.9 2603.25   450.9 2610.77  527.36 2610.82  529.46 2610.82
  660.05 2609.92  678.66 2609.53   728.4 2608.77  790.64 2633.63     805 2635.76
  829.97 2632.92   839.4  2636.3   864.5 2654.12  903.18  2663.3   932.8 2670.01
#Mann= 13 ,-1 , 0
       0      .1       0  268.28    .055       0   296.8    .045       0
   297.2    .045       0   330.7    .055       0  398.87    .035       0
  527.36     .02       0  529.46    .025       0  660.05      .1       0
  678.66    .035       0  790.64    .055       0  829.97     .06       0
  903.18      .1       0
Bank Sta=297.2,330.7
XS Rating Curve= 0 ,0
Exp/Cntr=0.3,0.1

Type RM Length L Ch R = 1 ,621     ,113.2,114.2,115.3
XS GIS Cut Line= 2
2067985.20590031371313.6273858942066863.90439503371163.579806525
#Sta/Elev= 30
       0 2626.25    70.4 2622.57   209.8 2605.95   355.1 2602.11   381.6  2597.9
   398.1 2590.62   404.7 2588.45   411.4  2587.5   445.8 2589.01   455.1 2591.57
   467.6 2594.97   477.6 2594.19   490.8 2588.73   537.6 2588.54   553.7 2590.83
   563.6 2595.17   570.2 2592.66   576.9 2595.26   603.3 2594.63   616.6 2595.68
   640.7 2608.69     653 2610.09     845 2608.86     941  2605.8   954.1 2609.51
   977.4 2621.96  1010.5 2620.39  1043.6 2644.58  1100.3 2660.75  1131.3 2669.36
#Mann= 11 ,-1 , 0
       0      .1       0   398.1    .045       0   404.7    .045       0
   445.8    .045       0   455.1    .035       0   455.1     .06       0
   603.3      .1       0     653    .025       0     845    .055       0
   977.4     .06       0  1100.3      .1       0
#XS Ineff= 2 , 0
                          466.55         2598.84
Permanent Ineff=
       F       F
Bank Sta=404.7,445.8
XS Rating Curve= 0 ,0
Exp/Cntr=0.3,0.1

Type RM Length L Ch R = 1 ,507     ,138.5,138.7,138.3
XS GIS Cut Line= 2
2068030.95471291371232.0619791412066895.08616242 371014.98487838
#Sta/Elev= 30
       0 2604.21   388.2 2601.12     435 2592.35   447.9 2585.47   458.3 2582.81
   478.4 2583.06   484.6 2585.87   491.7 2592.36   501.8 2593.76   508.4 2592.94
   521.8  2585.4   548.5 2584.84   560.8 2585.65   574.8 2592.81   685.5 2592.34
   785.7 2594.35   796.3 2596.08   815.7 2591.31   835.6 2592.13   855.2 2596.69
   916.9 2602.65   969.4 2598.96   982.8 2603.75   999.5 2610.03  1012.8 2611.72
  1062.9 2608.95  1076.3 2614.57  1099.2 2630.65  1125.1 2637.32  1156.4 2644.08
#Mann= 10 ,-1 , 0
       0      .1       0   447.9    .045       0   484.6      .1       0
   548.5    .035       0   574.8     .06       0   685.5      .1       0
   785.7    .025       0   835.6    .055       0   982.8     .06       0
  1125.1      .1       0
#XS Ineff= 2 , 0
                          502.29         2595.93
Permanent Ineff=
       F       F
Bank Sta=447.9,484.6
XS Rating Curve= 0 ,0
Exp/Cntr=0.5,0.3

Type RM Length L Ch R = 1 ,368     ,120.7,120.5,118.9
XS GIS Cut Line= 3
2068093.40306295371100.3049589032067156.80058495370927.180656131
2067001.26987782370976.346620695
#Sta/Elev= 30
       0 2598.88    64.2 2600.16    74.2 2598.69   134.3  2598.3     191  2597.6
   244.4 2596.15   344.5 2594.05   403.8 2589.93   452.9 2590.52   474.6 2587.92
   484.6 2583.94   489.9 2581.64     508 2579.21   529.5 2581.69   544.7 2590.57
   555.3 2592.42     578 2592.38   598.1 2588.44   661.3 2587.88   841.6 2584.25
   898.3  2580.7   909.1 2581.55   931.6 2588.64   941.7 2589.93   973.3 2588.99
    1024 2589.28  1030.7 2590.82  1051.5  2600.7  1072.6 2605.18  1115.6 2605.17
#Mann= 11 ,-1 , 0
       0     .05       0   134.3     .06       0     191    .055       0
   244.4      .1       0   452.9    .055       0   484.6    .055       0
   489.9    .045       0   529.5    .055       0   555.3     .06       0
   661.3    .055       0   973.3     .06       0
#XS Ineff= 2 , 0
          474.69 2588.12  539.34            2588
Permanent Ineff=
       F       F
Bank Sta=489.9,529.5
XS Rating Curve= 0 ,0
Exp/Cntr=0.5,0.3

Type RM Length L Ch R = 1 ,248     ,102.7,102.7,102.7
XS GIS Cut Line= 4
2068120.38638338370970.1636248382067479.20777994370871.305978188
2067254.53030394370875.1850683192067010.07630315370934.474002489
#Sta/Elev= 30
       0  2583.7   154.3 2582.31   174.2 2580.58   204.1 2582.53   350.1 2583.46
   393.3 2578.66   413.2 2580.69     463 2580.82   469.6 2582.59   479.82578.821
   486.2 2577.18   512.8 2576.77   521.6  2578.9   527.5 2582.07   549.3 2583.26
   609.1 2581.48     629 2582.64   678.6 2580.14   750.6 2583.89   788.3 2583.38
   825.2 2586.16   843.1 2585.53   865.7 2581.33   919.3 2581.89     943 2576.57
   997.3  2590.2  1046.3 2591.63  1071.2 2596.98  1084.7 2602.38    1125 2600.96
#Mann= 8 ,-1 , 0
       0    .055       0  177.46     .06       0  272.53    .055       0
   479.7    .045       0   521.5    .045       0   524.9     .06       0
   585.7    .055       0  692.04     .06       0
#XS Ineff= 2 , 0
          320.73 2585.58  562.31          2585.4
Permanent Ineff=
       F       F
Bank Sta=479.8,521.6
XS Rating Curve= 0 ,0
Exp/Cntr=0.5,0.3

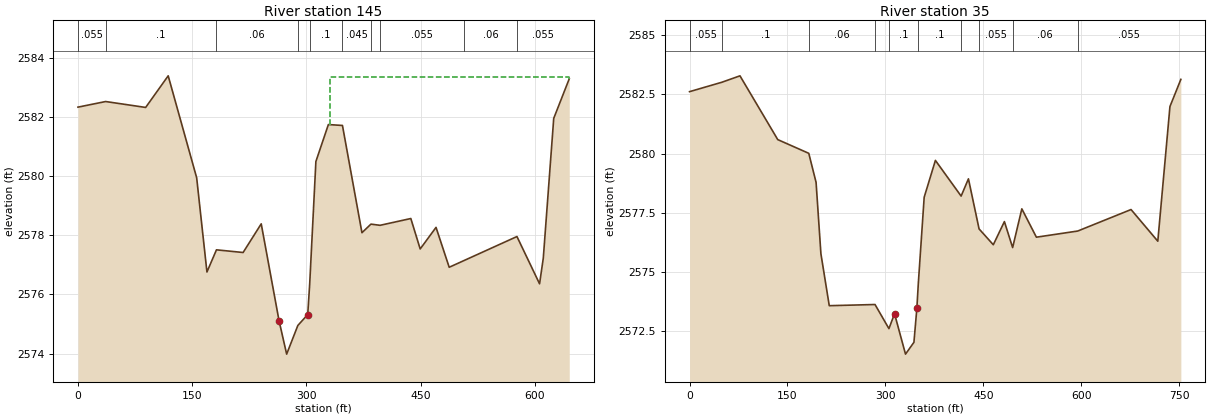
Type RM Length L Ch R = 1 ,145     ,110.2,110.2,110.2
XS GIS Cut Line= 4
2067902.92438944370919.3537986422067828.90418971370843.190948809
2067525.56926767370763.0638342262067320.97631165370857.615931958
#Sta/Elev= 30
       0 2582.34    36.3 2582.53    88.9 2582.33   118.5  2583.4   155.9 2579.95
   169.4 2576.76   181.9 2577.51   216.9 2577.42   240.7 2578.39   264.12575.111
   274.1 2573.98   288.8 2574.95   301.8 2575.32   301.8 2575.33   304.4 2576.37
   312.5  2580.5   328.9 2581.75   347.4 2581.72     373 2578.09   384.8 2578.38
   396.8 2578.34   437.2 2578.57   449.5 2577.54   470.3 2578.27   487.6 2576.92
   576.6 2577.96   606.3 2576.36   611.2 2577.23   624.9 2581.96   645.3  2583.3
#Mann= 10 ,-1 , 0
       0    .055       0    36.3      .1       0   181.9     .06       0
   288.8    .055       0   304.4      .1       0   347.4    .045       0
   384.8      .1       0   396.8    .055       0   507.2     .06       0
   576.6    .055       0
#XS Ineff= 2 , 0
                          331.06         2583.37
Permanent Ineff=
       F       F
Bank Sta=264.1,301.8
XS Rating Curve= 0 ,0
Exp/Cntr=0.3,0.1

Type RM Length L Ch R = 1 ,35      ,,,
XS GIS Cut Line= 4
2067930.98140044370907.5835746132067801.88086089370775.226516522
2067643.79627801 370670.834016242067310.17855686370849.052513079
#Sta/Elev= 30
       0 2582.62    49.7 2583.02    77.2 2583.29   135.1 2580.59   182.6 2580.01
   193.8 2578.78   201.2 2575.76     214 2573.56   284.1 2573.61   305.4 2572.59
     3142573.219   330.8 2571.51   343.7 2572.01   348.2 2573.45   350.4 2574.49
   359.4 2578.15   376.6 2579.71     416  2578.2   427.2 2578.93   443.5 2576.81
   465.3 2576.14   482.3 2577.12   494.9 2576.02     509 2577.66   531.3 2576.46
   594.6 2576.72   676.3 2577.63   717.3 2576.29   735.9 2581.99   752.6 2583.14
#Mann= 10 ,-1 , 0
       0    .055       0    49.7      .1       0   182.6     .06       0
   284.1    .055       0   305.4      .1       0   350.4      .1       0
     416    .045       0   443.5    .055       0   494.9     .06       0
   594.6    .055       0
Bank Sta=314,348.2
XS Rating Curve= 0 ,0
Exp/Cntr(USF)=0,0
Exp/Cntr=0.3,0.1
LCMann Table=0

Chan Stop Cuts=-1
Use User Specified Reach Order=0
Composite Channel Slope=5